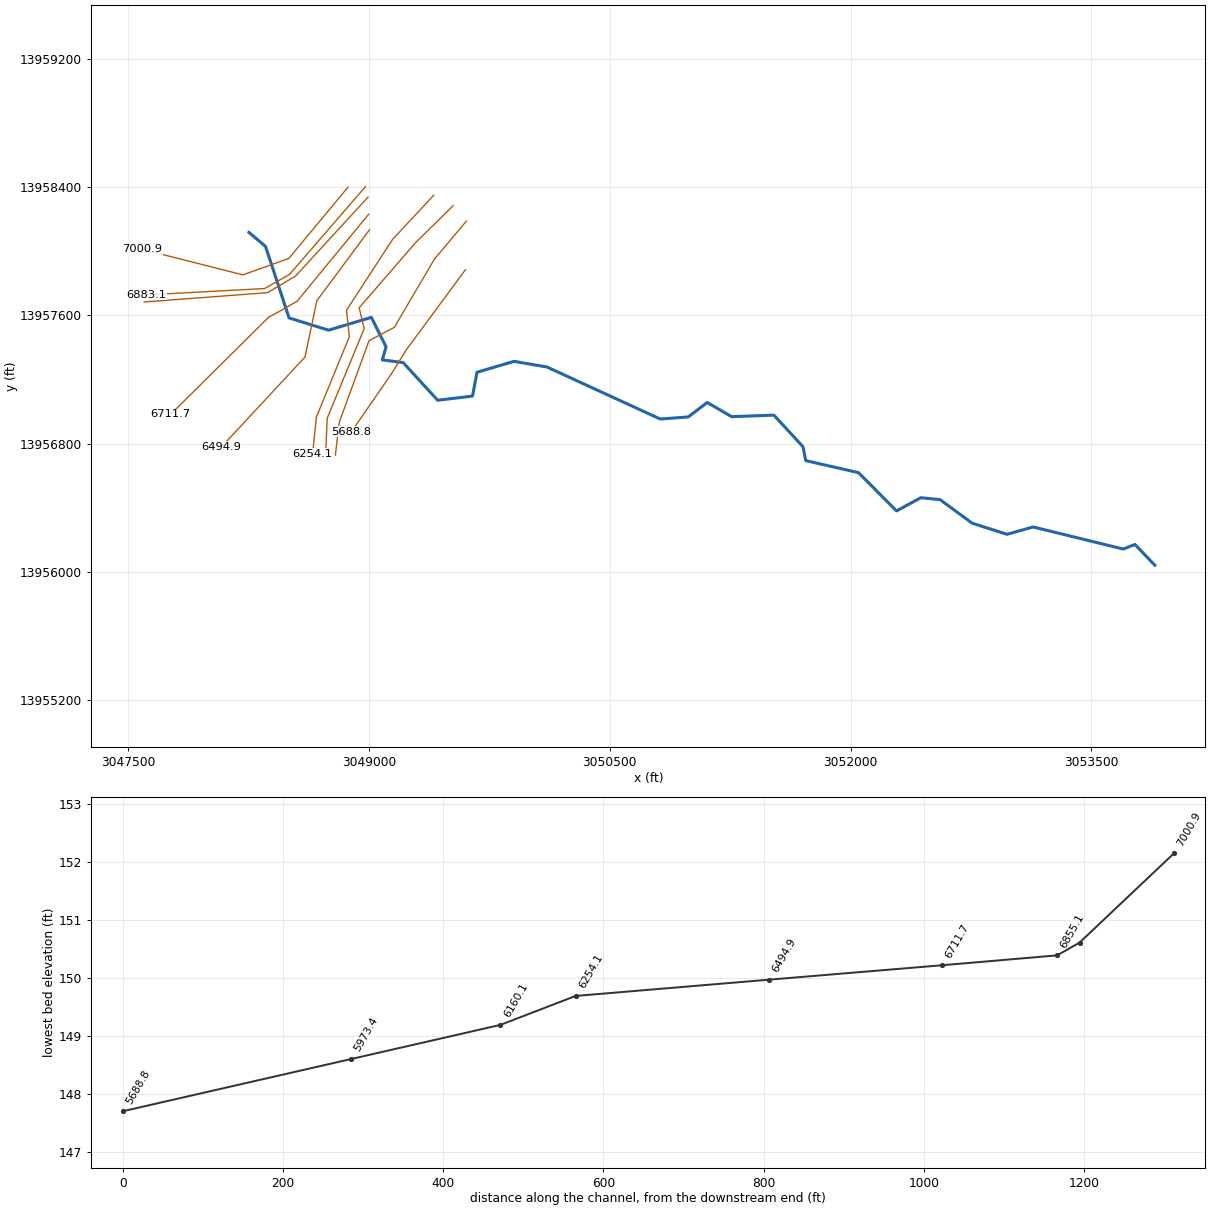
--- M116-00-00.PRJ (project) ---

Proj Title=M116-00-00
Current Plan=p03
Default Exp/Contr=.3,.1
English Units
Geom File=g01
Flow File=f02
Flow File=f03
Plan File=p02
Plan File=p03
Y Axis Title=Elevation
X Axis Title(PF)=Main Channel Distance
X Axis Title(XS)=Station
BEGIN DESCRIPTION:
Willow Creek
Tributary 8.16 to Willow Creek
HCFCD Unit M116-00-00
Flood Hazard Model
10, 2, 1, 0.2% Event
Filename M116-00-00.prj
Prepared by: Halff Associates, Inc  Date: 03/05/2004
Reviewed by:                  Date:
STATUS Final RAS
END DESCRIPTION:
DSS Export Rating Curves= 0
DSS Export Rating Curve Sorted= 0
DSS Export Volume Flow Curves= 0
DXF OffsetX= 0
DXF OffsetY= 0
DXF ScaleX= 1
DXF ScaleY= 10

--- M116-00-00.p03 (plan) ---

Plan Title=Floodway
Program Version=3.11
Short Identifier=Floodway0607
Geom File=g01
Flow File=f03
Subcritical Flow
K Sum by GR= 0
Std Step Tol= 0.01
Critical Tol= 0.01
Num of Std Step Trials= 20
Max Error Tol= 0.3
Flow Tol Ratio= 0.001
Split Flow NTrial= 30
Split Flow Tol= 0.02
Split Flow Ratio= 0.02
Log Output Level= 0
Friction Slope Method= 1
Unsteady Friction Slope Method= 2
Unsteady Bridges Friction Slope Method= 1
Parabolic Critical Depth
Global Vel Dist= 0 , 0 , 0
Global Log Level= 0
CheckData=True
Encroach Param=-1 ,0,0, 2
Encroach River=M116-00-00
Encroach Reach=M116-00-00_0007
Encroach Node=7000.9
       1  4961.7  5020.2
Encroach Node=6883.1
       1    4945    5030
Encroach Node=6869.1
       1    4945    5030
Encroach Node=6855.1
       1    4970    5030
Encroach Node=6711.7
       1  4913.6  5075.1
Encroach Node=6494.9
       1  4870.2  5239.7
Encroach Node=6254.1
       1    4970    5270
Encroach Node=6207.1
       1    4970    5270
Encroach Node=6160.1
       1    4970    5300
Encroach Node=5973.4
       1  4965.7    5161
Encroach Node=5688.8
       1    4970    5140
Encroach Node=5674.8
       1    4970    5140
Encroach Node=5660.8
       1    4970    5140
Encroach Node=5433
       1    4920    5050
Encroach Node=5407.0
       1    4920    5025
Encroach Node=5393.0
       1    4920    5025
Encroach Node=5379.0
       1    4920    5025
Encroach Node=5138.5
       1    4890    5040
Encroach Node=5125.0
       1    4890    5040
Encroach Node=5111.5
       1    4890    5040
Encroach Node=4779.6
       1 4927.01    5100
Encroach Node=4761.1
       1 4927.01    5100
Encroach Node=4742.6
       1 4927.01    5100
Encroach Node=4544.8
       1 4922.33    5120
Encroach Node=4528.7
       1    4920    5125
Encroach Node=4507.7
       1    4920    5125
Encroach Node=4486.7
       1    4920    5130
Encroach Node=4457.1
       1 4914.96    5120
Encroach Node=4440.6
       1 4914.96    5120
Encroach Node=4424.1
       1  4914.6    5120
Encroach Node=4277.8
       1    4950    5100
Encroach Node=4263.8
       1    4965    5075
Encroach Node=4249.8
       1    4980    5040
Encroach Node=4164.2
       1    4980    5040
Encroach Node=3947.4
       1    4964    5060
Encroach Node=3699.1
       1    4974    5115
Encroach Node=3372
       1    4974 5114.69
Encroach Node=3023.0
       1    4905    5110
Encroach Node=2871.6
       1    4905 5068.89
Encroach Node=2742.6
       1    4905    5110
Encroach Node=2717.6
       1    4905    5110
Encroach Node=2692.6
       1    4905    5110
Encroach Node=2579.8
       1    4855    5060
Encroach Node=1485.9
       1    4820    5115
Encroach Node=706.6
       1    4435    5460
Computation Interval=1HOUR
Output Interval=1HOUR
Run HTab= 0
Run UNet= 0
Run PostProcess= 0
UNET Theta= 1
UNET Theta Warmup= 1
UNET ZTol= 0.02
UNET ZSATol= 0.1
UNET MxIter= 20
UNET MaxInSteps= 20
UNET DtIC= 0
UNET DtMin= 0
UNET MaxCRTS= 20
UNET WFStab= 2
UNET SFStab= 1
UNET WFX= 1
UNET SFX= 1
UNET DSS MLevel= 4
UNET DZMax Abort= 100
UNET Convert EG Bridges=-1
UNET Use Existing IB Tables=-1
UNET Froude Reduction=False
UNET Froude Limit= 1
UNET Froude Power= 10
Instantaneous Interval=1HOUR
Write IC File= 0
Echo Input=False
Echo Output=False
Write Detailed= 0
Detailed Automatic Start=False, 10

--- M116-00-00.p02 (plan) ---

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Plan Title=FEMA Effective June 2007
Program Version=3.13
Short Identifier=FEMAeff0607
Geom File=g01
Flow File=f02
Encroach Param=-1 ,0,0, 0

--- M116-00-00.f03 (steady flow) ---

Flow Title=Floodway
Program Version=3.13
Number of Profiles= 2
Profile Names=1PCT_100yr,1PCTFloodway_100yrFW
River Rch & RM=M116-00-00,M116-00-00_0007       ,7000.9
    1100    1100
River Rch & RM=M116-00-00,M116-00-00_0007       ,6494.9
    1200    1200
River Rch & RM=M116-00-00,M116-00-00_0007       ,5973.4
    1320    1320
River Rch & RM=M116-00-00,M116-00-00_0007       ,5407
    1380    1380
River Rch & RM=M116-00-00,M116-00-00_0007       ,5138.5
    1470    1470
River Rch & RM=M116-00-00,M116-00-00_0007       ,4779.6
    1560    1560
River Rch & RM=M116-00-00,M116-00-00_0007       ,4457.1
    1640    1640
River Rch & RM=M116-00-00,M116-00-00_0007       ,4164.2
    1700    1700
River Rch & RM=M116-00-00,M116-00-00_0007       ,3947.4
    1860    1860
River Rch & RM=M116-00-00,M116-00-00_0007       ,2871.6
    1900    1900
River Rch & RM=M116-00-00,M116-00-00_0007       ,2579.8
    1910    1910
Boundary for River Rch & Prof#=M116-00-00,M116-00-00_0007       , 1
Up Type= 0
Dn Type= 3
Dn Slope=0.0028
Boundary for River Rch & Prof#=M116-00-00,M116-00-00_0007       , 2
Up Type= 0
Dn Type= 1
Dn Known WS=141.69
DSS Import GetInterval= 0
DSS Import GetPeak= 0
DSS Import FillOption= 0

--- M116-00-00.f02 (steady flow) ---

Flow Title=FEMA Effective June 2007
Program Version=3.13
Number of Profiles= 4
Profile Names=10PCT_10yr, 2PCT_50yr, 1PCT_100yr,0.2PCT_500yr
River Rch & RM=M116-00-00,M116-00-00_0007 ,7000.9
     550     880    1100    1640
River Rch & RM=M116-00-00,M116-00-00_0007 ,6494.9
     600     970    1200    1780
River Rch & RM=M116-00-00,M116-00-00_0007 ,5973.4
     660    1070    1320    1960
River Rch & RM=M116-00-00,M116-00-00_0007 ,5407
     690    1130    1380    2050
River Rch & RM=M116-00-00,M116-00-00_0007 ,5138.5
     740    1200    1470    2180
River Rch & RM=M116-00-00,M116-00-00_0007 ,4779.6
     780    1280    1560    2300
River Rch & RM=M116-00-00,M116-00-00_0007 ,4457.1
     820    1350    1640    2410
River Rch & RM=M116-00-00,M116-00-00_0007 ,4164.2
     850    1400    1700    2500
River Rch & RM=M116-00-00,M116-00-00_0007 ,3947.4
     930    1560    1860    2730
River Rch & RM=M116-00-00,M116-00-00_0007 ,2871.6
     950    1600    1900    2800
River Rch & RM=M116-00-00,M116-00-00_0007 ,2579.8
     994    1607    1910    2832
Boundary for River Rch & Prof#=M116-00-00,M116-00-00_0007 , 1
Up Type= 0
Dn Type= 3
Dn Slope=0.0028
Boundary for River Rch & Prof#=M116-00-00,M116-00-00_0007 , 2
Up Type= 0
Dn Type= 3
Dn Slope=0.0028
Boundary for River Rch & Prof#=M116-00-00,M116-00-00_0007 , 3
Up Type= 0
Dn Type= 3
Dn Slope=0.0028
Boundary for River Rch & Prof#=M116-00-00,M116-00-00_0007 , 4
Up Type= 0
Dn Type= 3
Dn Slope=0.0028
DSS Import GetInterval= 0
DSS Import GetPeak= 0
DSS Import FillOption= 0

--- M116-00-00.g01 (geometry) ---

Geom Title=M116-00-00 June 2007
Program Version=3.13

River Reach=M116-00-00      ,M116-00-00_0007
Reach XY= 30
      3048253.28     13958118.05      3048356.58     13958030.37
      3048503.28     13957584.19      3048748.94      13957507.8
      3049015.43     13957587.67      3049107.44     13957403.64
      3049084.01     13957322.04      3049213.71     13957305.49
      3049428.62      13957070.3      3049645.64     13957096.35
      3049673.73     13957244.97      3049904.12     13957312.99
      3050108.47     13957278.22      3050814.91     13956953.12
      3050989.39     13956966.14      3051107.44     13957056.42
      3051259.35     13956967.87      3051522.37     13956977.42
       3051703.8     13956780.37      3051721.16     13956693.57
      3052050.15     13956618.05      3052286.26     13956379.33
       3052437.3      13956461.8       3052557.2      13956450.1
      3052757.62     13956302.94      3052974.63      13956233.5
      3053136.96      13956279.5      3053698.59     13956141.48
      3053771.51     13956170.13      3053894.77     13956040.79

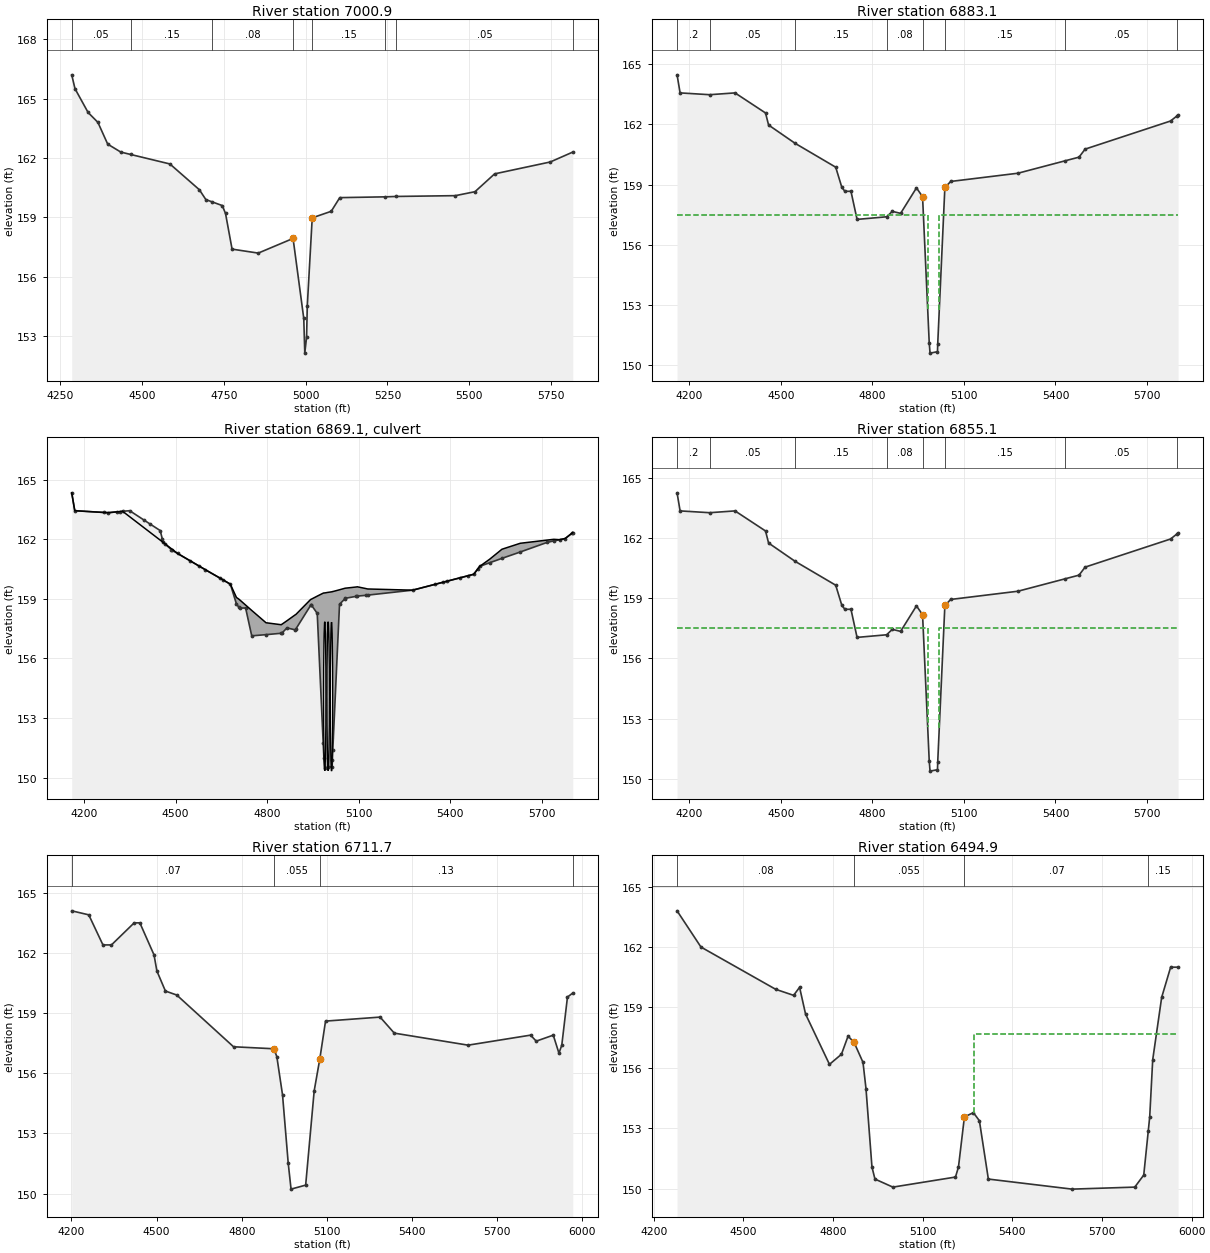
Type RM Length L Ch R = 1 ,7000.9  ,65.8,117.8,77.5
BEGIN DESCRIPTION:
Cross Section 7000.9
Cross Section XS-09
END DESCRIPTION:
XS GIS Cut Line= 4
      3048870.59       13958401.      3048501.21       13957955.
      3048215.68       13957853.      3047586.84      13958012.7
#Sta/Elev= 30
  4285.3   166.2  4295.3   165.5  4335.3   164.3  4365.3   163.8  4395.3   162.7
  4435.3   162.3  4465.3  162.18  4585.3   161.7  4675.3   160.4  4695.3   159.9
  4715.3  159.78  4745.3   159.6  4755.3   159.2  4775.3   157.4  4855.3   157.2
  4961.7  157.94  4994.4   153.9  4997.5  152.15    5003  152.96  5005.2  154.55
  5020.2  158.98  5078.3  159.31  5104.4     160  5243.8  160.04  5277.1  160.06
  5457.6   160.1  5517.6   160.3  5577.6   161.2  5747.6   161.8  5816.4   162.3
#Mann= 8 , 1 , 0
  4285.3     .05       0  4465.3     .15       0  4715.3     .08       0
  4961.7    .055       0  5020.2     .15       0  5243.8     .12       0
  5277.1     .05       0  5816.4      .2       0
Bank Sta=4961.7,5020.2
Exp/Cntr=0.5,0.3

Type RM Length L Ch R = 1 ,6883.1  ,28,28,28
BEGIN DESCRIPTION:
Upstream Section of Tomball Country Club Road Culvert
END DESCRIPTION:
XS GIS Cut Line= 4
      3048979.58      13958404.4      3048506.01      13957855.8
      3048350.53      13957767.6      3047616.53       13957728.
#Sta/Elev= 30
  4159.6  164.47  4169.6  163.57  4266.4  163.48  4349.6  163.57  4449.6  162.57
  4459.6  161.97  4546.4  161.06  4679.6  159.87  4699.6  158.87  4709.6  158.67
  4729.6  158.67  4749.6  157.27  4846.4   157.4  4865.1  157.67  4892.3  157.57
  4944.3  158.84  4964.3   158.4  4986.1  151.13  4988.8  150.61  5013.2  150.68
  5013.9  151.04  5037.4  158.86  5056.6  159.16  5277.1  159.57    5432  160.19
  5477.1  160.37  5497.1  160.77  5777.1  162.17  5799.5  162.44  5801.9  162.47
#Mann= 8 ,-1 , 0
  4159.6      .2       0  4266.4     .05       0  4546.4     .15       0
  4846.4     .08       0  4964.3    .055       0  5037.4     .15       0
    5432     .05       0  5799.5      .2       0
#XS Ineff= 2 , 0
       0    4981   157.5    5019       0   157.5
Permanent Ineff=
       F       F
Bank Sta=4964.3,5037.4
Exp/Cntr=0.5,0.3

Type RM Length L Ch R = 2 ,6869.1  ,,,
BEGIN DESCRIPTION:
TOMBALL COUNTRY CLUB ROAD
Cross Section 6869.1
Structure ID: M116-00-00-10
END DESCRIPTION:
Bridge Culvert--1,0,-1,-1, 0
Deck Dist Width WeirC Skew NumUp NumDn MinLoCord MaxHiCord MaxSubmerge Is_Ogee
10,8,2.6,0, 61, 61, , , 0.95, 0, 1,1,,
  4159.6  4169.6  4266.4  4279.6  4306.4  4316.4  4326.4  4506.4  4546.4  4576.4
  4596.4  4646.4  4656.4  4679.6  4699.6  4706.4  4709.6  4729.6  4749.6  4796.4
  4846.4  4848.1  4865.1  4892.3  4894.5  4942.6  4944.3  4964.3  4983.9  4986.1
  4988.8  4999.8  5000.3  5013.2  5013.9  5015.4  5037.4    5056  5056.6  5092.2
  5095.6    5124  5129.7  5277.1  5349.7  5377.1  5389.7    5432  5459.7  5477.1
  5489.7  5497.1  5529.7  5569.7  5629.7  5717.1  5739.7  5759.7  5777.1  5799.5
  5801.9
  164.34  163.44  163.35  163.34  163.38  163.39  163.41  161.29  160.93  160.66
  160.48  160.04  159.95  159.74  159.07     159  158.96  158.69  158.42   157.8
   157.7  157.72   157.9   158.2  158.22  158.97  158.98  159.14  159.29   159.3
   159.3  159.33  159.33  159.36  159.37  159.37  159.46  159.54  159.54   159.6
  159.61  159.52   159.5  159.44  159.73  159.84  159.89  160.06  160.17  160.24
  160.49  160.64     161   161.5   161.8  161.96     162  161.98  162.04  162.31
  162.34
                                                                                
                                                                                
                                                          158.27  151.73     151
  150.48  150.53  150.53  150.55  150.91  151.41  158.73
                                                                                
                                                                                
        
  4159.6  4169.6  4266.4  4279.6  4306.4  4316.4  4326.4  4506.4  4546.4  4576.4
  4596.4  4646.4  4656.4  4679.6  4699.6  4706.4  4709.6  4729.6  4749.6  4796.4
  4846.4  4848.1  4865.1  4892.3  4894.5  4942.6  4944.3  4964.3  4983.9  4986.1
  4988.8  4999.8  5000.3  5013.2  5013.9  5015.4  5037.4    5056  5056.6  5092.2
  5095.6    5124  5129.7  5277.1  5349.7  5377.1  5389.7    5432  5459.7  5477.1
  5489.7  5497.1  5529.7  5569.7  5629.7  5717.1  5739.7  5759.7  5777.1  5799.5
  5801.9
   164.3   163.4  163.32  163.31  163.35  163.36  163.38  161.26   160.9  160.63
  160.45  160.01  159.92  159.71  159.07     159  158.96  158.69  158.42   157.8
   157.7  157.72   157.9   158.2  158.22  158.97  158.98  159.14  159.29   159.3
   159.3  159.33  159.33  159.36  159.37  159.37  159.46  159.54  159.54   159.6
  159.61  159.52   159.5  159.41   159.7  159.81  159.86  160.03  160.14  160.21
  160.46  160.61     161   161.5   161.8  161.96     162  161.95  162.01  162.28
   162.3
                                                                                
                                                                                
                                                          158.19  151.65  150.92
   150.4  150.45  150.45  150.47  150.83  151.33  158.65
                                                                                
                                                                                
        
BR Coef= 1 , 0 , 0 ,1.25, 0 ,,,0.8,-1,2,1,
WSPro=,,,, 1 ,,,, 0 ,,,, 0 ,,,,-1 ,-1 ,-1 , 0 , 0 , 0 , 0 , 0
Culvert=1,7.5,,8,0.025,0.4,1,1,3,150.35,4989,150.16,4989,Culvert #1  , 0 ,10
Culvert Bottom n=0.025
Culvert=1,7.5,,8,0.05,0.4,1,1,3,150.35,5000.1,150.22,5000.1,Culvert #2  , 0 ,10
Culvert Bottom n=0.05
Culvert=1,7.5,,8,0.05,0.4,1,1,3,150.33,5011.2,150.24,5011.2,Culvert #3  , 0 ,10
Culvert Bottom n=0.05
BR U #Sta/Elev= 70
  4159.6  164.34  4169.6  163.44  4266.4  163.35  4279.6  163.34  4306.4  163.38
  4316.4  163.39  4326.4  163.41  4349.6  163.44  4396.4  162.97  4416.4  162.77
  4449.6  162.44  4456.4  162.03  4459.6  161.84  4466.4  161.75  4486.4  161.48
  4489.6  161.44  4506.4  161.29  4546.4  160.93  4576.4  160.66  4596.4  160.48
  4646.4  160.04  4656.4  159.95  4679.6  159.74  4699.6  158.74  4706.4   158.6
  4709.6  158.54  4729.6  158.54  4749.6  157.14  4796.4   157.2  4846.4  157.27
  4848.1  157.27  4865.1  157.54  4892.3  157.44  4894.5  157.49  4942.6  158.67
  4944.3  158.71  4964.3  158.27  4983.9  151.73  4986.1     151  4988.8  150.48
  4999.8  150.53  5000.3  150.53  5013.2  150.55  5013.9  150.91  5015.4  151.41
  5037.4  158.73    5056  159.02  5056.6  159.03  5092.2  159.13  5095.6  159.14
    5124  159.18  5129.7  159.19  5277.1  159.44  5349.7  159.73  5377.1  159.84
  5389.7  159.89    5432  160.06  5459.7  160.17  5477.1  160.24  5489.7  160.49
  5497.1  160.64  5529.7  160.82  5569.7  161.04  5629.7  161.36  5717.1  161.84
  5739.7  161.92  5759.7  161.98  5777.1  162.04  5799.5  162.31  5801.9  162.34
BR U #Mann= 8
  4159.6      .2  4266.4     .05  4546.4     .15  4846.4     .08  4964.3    .055
  5037.4     .15    5432     .05  5799.5      .2
BR U Banks=4964.3,5037.4
BR D #Sta/Elev= 70
  4159.6  164.26  4169.6  163.36  4266.4  163.27  4279.6  163.26  4306.4   163.3
  4316.4  163.31  4326.4  163.33  4349.6  163.36  4396.4  162.89  4416.4  162.69
  4449.6  162.36  4456.4  161.95  4459.6  161.76  4466.4  161.67  4486.4   161.4
  4489.6  161.36  4506.4  161.21  4546.4  160.85  4576.4  160.58  4596.4   160.4
  4646.4  159.96  4656.4  159.87  4679.6  159.66  4699.6  158.66  4706.4  158.52
  4709.6  158.46  4729.6  158.46  4749.6  157.06  4796.4  157.12  4846.4  157.19
  4848.1  157.19  4865.1  157.46  4892.3  157.36  4894.5  157.41  4942.6  158.59
  4944.3  158.63  4964.3  158.19  4983.9  151.65  4986.1  150.92  4988.8   150.4
  4999.8  150.45  5000.3  150.45  5013.2  150.47  5013.9  150.83  5015.4  151.33
  5037.4  158.65    5056  158.94  5056.6  158.95  5092.2  159.05  5095.6  159.06
    5124   159.1  5129.7  159.11  5277.1  159.36  5349.7  159.65  5377.1  159.76
  5389.7  159.81    5432  159.98  5459.7  160.09  5477.1  160.16  5489.7  160.41
  5497.1  160.56  5529.7  160.74  5569.7  160.96  5629.7  161.28  5717.1  161.76
  5739.7  161.84  5759.7   161.9  5777.1  161.96  5799.5  162.23  5801.9  162.26
BR D #Mann= 8
  4159.6      .2  4266.4     .05  4546.4     .15  4846.4     .08  4964.3    .055
  5037.4     .15    5432     .05  5799.5      .2
BR D Banks=4964.3,5037.4
BC Design=,, 0 ,, 0 ,,,,,,
BC HTab HWMax=164.47

Type RM Length L Ch R = 1 ,6855.1  ,140,143.4,170
BEGIN DESCRIPTION:
Downstream Section of Tomball Country Club Road Culvert
END DESCRIPTION:
XS GIS Cut Line= 4
    3048994.6821   13958337.9374      3048542.72      13957844.9
      3048369.55      13957741.9    3047600.9655   13957683.7439
#Sta/Elev= 30
  4159.6  164.25  4169.6  163.35  4266.4  163.26  4349.6  163.35  4449.6  162.35
  4459.6  161.75  4546.4  160.84  4679.6  159.65  4699.6  158.65  4709.6  158.45
  4729.6  158.45  4749.6  157.05  4846.4  157.18  4865.1  157.45  4892.3  157.35
  4944.3  158.62  4964.3  158.18  4986.1  150.91  4988.8  150.39  5013.2  150.46
  5013.9  150.82  5037.4  158.64  5056.6  158.94  5277.1  159.35    5432  159.97
  5477.1  160.15  5497.1  160.55  5777.1  161.95  5799.5  162.22  5801.9  162.25
#Mann= 8 ,-1 , 0
  4159.6      .2       0  4266.4     .05       0  4546.4     .15       0
  4846.4     .08       0  4964.3    .055       0  5037.4     .15       0
    5432     .05       0  5799.5      .2       0
#XS Ineff= 2 , 0
       0    4981   157.5    5019       0   157.5
Permanent Ineff=
       F       F
Bank Sta=4964.3,5037.4
Exp/Cntr=0.5,0.3

Type RM Length L Ch R = 1 ,6711.7  ,179.31,216.8,361.72
BEGIN DESCRIPTION:
Cross Section XS08.5
END DESCRIPTION:
XS GIS Cut Line= 6
      3048998.49      13958231.1      3048552.96      13957687.8
       3048481.4      13957646.9      3048456.16      13957632.4
      3048375.46       13957588.      3047766.16      13956982.9
#Sta/Elev= 30
  4201.1   164.1  4261.1   163.9  4311.1   162.4  4341.1   162.4  4421.1   163.5
  4441.1   163.5  4491.1   161.9  4501.1   161.1  4531.1   160.1  4571.1   159.9
  4771.1  157.32  4913.6  157.22  4923.7  156.82  4943.7  154.92  4963.7  151.52
  4973.7  150.22  5025.2  150.42  5055.2  155.12  5075.1  156.72  5095.2   158.6
  5287.4   158.8  5337.4     158  5597.4   157.4  5817.4   157.9  5837.4   157.6
  5897.4   157.9  5917.4     157  5927.4   157.4  5947.4   159.8  5966.1     160
#Mann= 4 ,-1 , 0
  4201.1     .07       0  4913.6    .055       0  5075.1     .13       0
  5966.1      .2       0
Bank Sta=4913.6,5075.1
Exp/Cntr=0.5,0.3

Type RM Length L Ch R = 1 ,6494.9  ,225.4,240.8,242.5
BEGIN DESCRIPTION:
Cross Section 6494.9
Cross Section XS-08-lake
END DESCRIPTION:
XS GIS Cut Line= 4
    3049004.2196   13958134.4108      3048676.37      13957691.8
       3048602.3      13957339.9      3048082.11      13956779.1
#Sta/Elev= 30
  4278.1   163.8  4358.1     162  4608.1   159.9  4668.1   159.6  4688.1     160
  4708.1  158.67  4788.1  156.17  4828.1  156.67  4850.3  157.57  4870.2  157.27
  4900.3  156.27  4910.3  154.97  4930.3  151.07  4940.3  150.47  5000.3  150.07
  5209.8  150.57  5219.8  151.07  5239.7  153.56  5269.8  153.77  5289.8  153.37
  5319.8  150.47  5599.8  149.97  5809.8  150.07  5839.8  150.67  5854.8  152.84
  5859.8  153.57  5869.8   156.4  5899.8   159.5  5929.8     161  5954.8     161
#Mann= 4 ,-1 , 0
  4278.1     .08       0  4870.2    .055       0  5239.7     .07       0
  5854.8     .15       0
#XS Ineff= 2 , 0
       0                 5270.63       0  157.66
Permanent Ineff=
       F       F
Bank Sta=4870.2,5239.7
Exp/Cntr=0.5,0.3

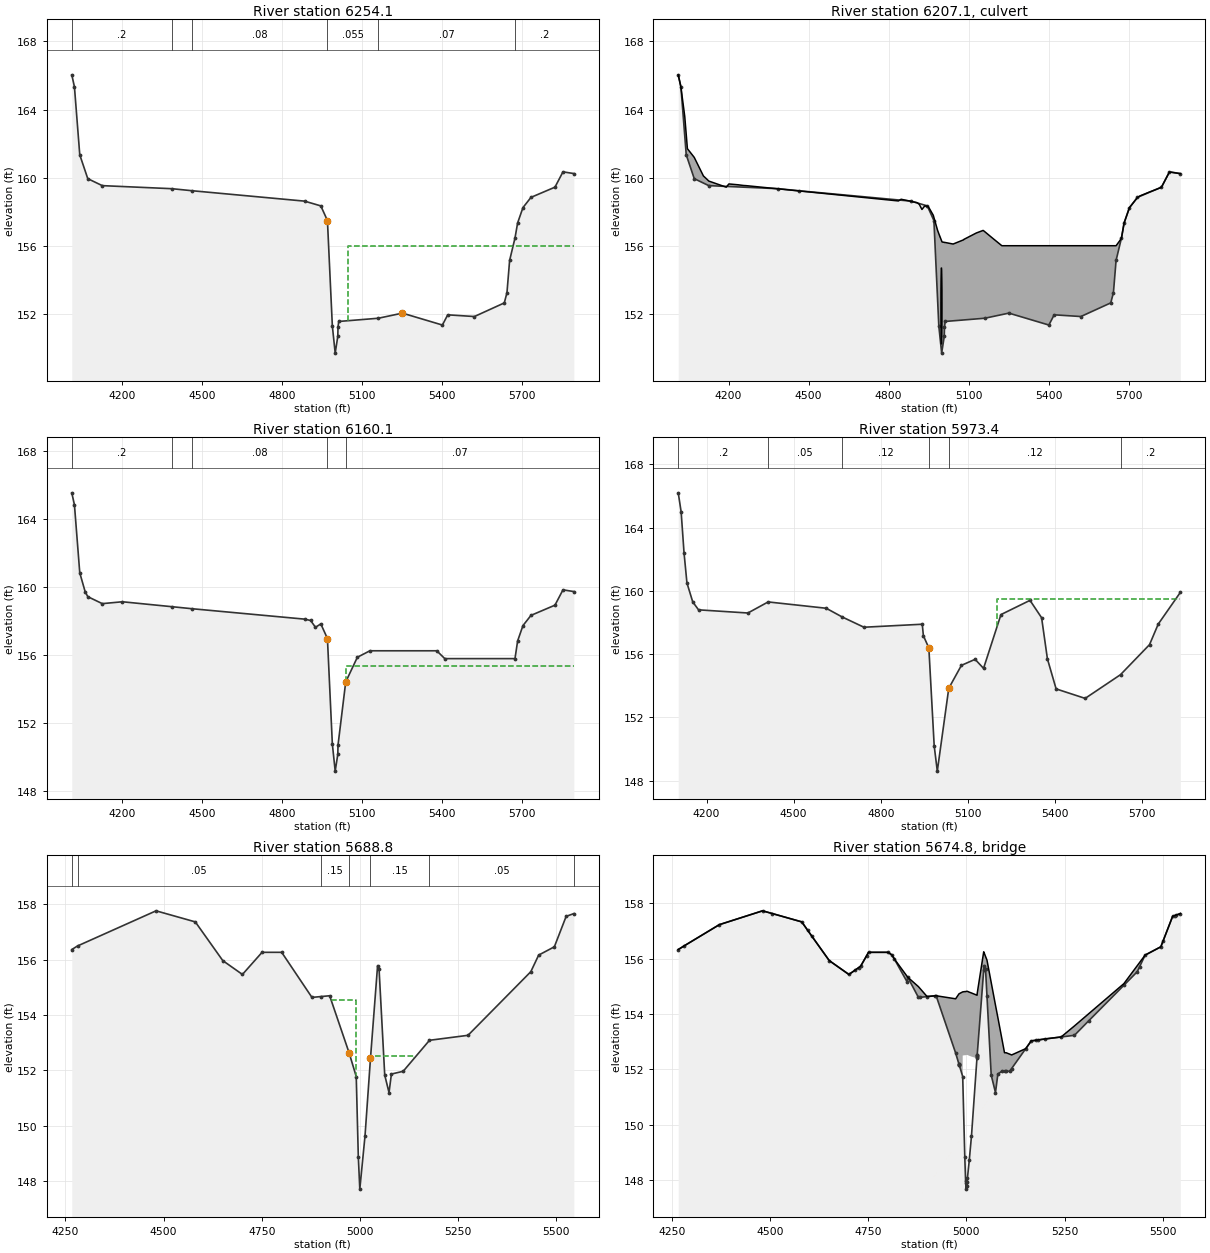
Type RM Length L Ch R = 1 ,6254.1  ,94,94,94
BEGIN DESCRIPTION:
Upstream Section of Golf Cart Bridge 600-ft D.S. of Tomball Country Club Road
END DESCRIPTION:
XS GIS Cut Line= 6
      3049404.41      13958350.1      3049148.39      13958075.2
      3048860.85      13957632.1       3048878.8      13957467.2
      3048673.53      13956965.4      3048649.63      13956736.1
#Sta/Elev= 30
  4011.3  166.04  4021.3  165.34  4041.3  161.34  4071.3  159.94  4125.7  159.53
    4387  159.35  4463.1  159.23  4884.1  158.62  4945.2  158.34    4970  157.48
  4988.4  151.29  4999.1  149.69  5008.8  150.67  5009.7  151.22  5012.3  151.55
  5161.1  151.74  5251.1  152.04  5401.1  151.34  5421.1  151.94  5521.1  151.84
  5633.2  152.64  5643.2  153.24  5653.2  155.14  5673.3  156.45  5683.2  157.34
  5703.2  158.24  5733.2  158.84  5823.2  159.44  5853.2  160.34    5894  160.24
#Mann= 6 ,-1 , 0
  4011.3      .2       0    4387     .05       0  4463.1     .08       0
    4970    .055       0  5161.1     .07       0  5673.3      .2       0
#XS Ineff= 2 , 0
       0    4960     156  5048.6       0     156
Permanent Ineff=
       F       F
Bank Sta=4970,5251.1
Exp/Cntr=0.5,0.3

Type RM Length L Ch R = 2 ,6207.1  ,,,
BEGIN DESCRIPTION:
GOLF CART BRIDGE 600FT DS TOMBALL COUNTRY CLUB RD
Cross Section 6207.1
Structure ID: M116-00-00-09
END DESCRIPTION:
Bridge Culvert--1,0,-1,-1, 0
Deck Dist Width WeirC Skew NumUp NumDn MinLoCord MaxHiCord MaxSubmerge Is_Ogee
10,74,3,0, 81, 81, , , 0.95, 0, 1,1,,
  4011.3  4021.3  4035.7  4041.3  4045.7  4061.3  4071.3  4105.7  4121.3  4125.7
  4191.3  4201.3  4235.7  4255.7  4265.7    4387  4463.1  4836.9  4846.9  4884.1
  4894.1  4906.9  4915.2  4925.2  4935.2  4945.2  4951.2  4967.7    4970  4983.9
  4988.4  4990.3  4992.5  4992.6  4999.1  5000.6  5008.8  5009.7  5012.3  5038.6
  5042.2  5081.7  5082.2  5129.3  5154.8  5161.1  5191.1  5224.8  5251.1  5311.1
  5351.1  5361.1  5401.1  5411.1  5421.1  5441.1  5451.1  5471.1  5521.1  5541.1
  5551.1  5571.1  5601.1  5611.1  5633.2  5643.2  5653.2  5673.2  5673.3  5683.2
  5703.2  5733.2  5743.2  5780.9  5800.9  5823.2  5830.9  5853.2  5853.8  5890.9
    5894
  166.03  165.33   163.6  162.54   161.7  161.39  161.19   160.1  159.87   159.8
  159.44  159.63  159.58  159.54  159.53  159.34  159.22  158.63  158.73  158.61
  158.57  158.53  158.43  158.13  158.33  158.33  158.24  157.79  157.66   156.9
  156.71  156.63  156.54  156.54  156.28  156.22   156.2  156.19  156.19  156.11
   156.1  156.35  156.37  156.75   156.9  156.82  156.43     156     156     156
     156     156     156     156     156     156     156     156     156     156
     156     156     156     156     156     156     156  156.43  156.44  157.33
  158.23  158.83  158.93  159.17  159.29  159.43  159.66  160.33  160.33  160.24
  160.23
                                                                                
                                                                                
                                                                                
                                                                                
                                                                                
                                                                                
                                                                                
                                                                                
        
  4011.3  4021.3  4035.7  4041.3  4045.7  4061.3  4071.3  4105.7  4121.3  4125.7
  4191.3  4201.3  4235.7  4255.7  4265.7    4387  4463.1  4836.9  4846.9  4884.1
  4894.1  4906.9  4915.2  4925.2  4935.2  4945.2  4951.2  4967.7    4970  4983.9
  4988.4  4990.3  4992.5  4992.6  4999.1  5000.6  5008.8  5009.7  5012.3  5038.6
  5042.2  5081.7  5082.2  5129.3  5154.8  5161.1  5191.1  5224.8  5251.1  5311.1
  5351.1  5361.1  5401.1  5411.1  5421.1  5441.1  5451.1  5471.1  5521.1  5541.1
  5551.1  5571.1  5601.1  5611.1  5633.2  5643.2  5653.2  5673.2  5673.3  5683.2
  5703.2  5733.2  5743.2  5780.9  5800.9  5823.2  5830.9  5853.2  5853.8  5890.9
    5894
  166.03  165.33   163.6  162.54   161.7  161.39  161.19   160.1  159.87   159.8
  159.44  159.63  159.58  159.54  159.53  159.34  159.22  158.63  158.73  158.61
  158.57  158.53  158.43  158.13  158.33  158.33  158.24  157.79  157.66   156.9
  156.71  156.63  156.54  156.54  156.28  156.22   156.2  156.19  156.19  156.11
   156.1  156.35  156.37  156.75   156.9  156.82  156.43     156     156     156
     156     156     156     156     156     156     156     156     156     156
     156     156     156     156     156     156     156  156.43  156.44  157.33
  158.23  158.83  158.93  159.17  159.29  159.43  159.66  160.33  160.33  160.24
  160.23
                                                                                
                                                                                
                                                                                
                                                                                
                                                                                
                                                                                
                                                                                
                                                                                
        
BR Coef= 1 , 0 , 0 ,1.25, 0 ,,,0.8,-1,2,1,
WSPro=,,,, 1 ,,,, 0 ,,,, 0 ,,,,-1 ,-1 ,-1 , 0 , 0 , 0 , 0 , 0
Culvert=1,4.5,,74,0.015,0.4,1,1,3,150.21,4998.3,150.2,4998.3,Culvert #1  , 0 ,10
Culvert Bottom n=0.015
BR D #Sta/Elev= 61
  4011.3  165.59  4021.3  164.89  4025.7  164.01  4035.7  162.01  4041.3  160.89
  4045.7  160.65  4061.3  159.79  4071.3  159.49  4095.7  159.29  4105.7  159.21
  4121.3  159.09  4125.7  159.08  4191.3  158.99  4201.3  159.19  4235.7  159.14
  4255.7   159.1  4265.7  159.09    4387   158.9  4463.1  158.78  4836.9  158.19
  4846.9  158.29  4884.1  158.17  4894.1  158.13  4906.9  158.09  4915.2  157.99
  4925.2  157.69  4935.2  157.89  4945.2  157.89  4951.2   157.8  4967.7  157.12
    4970  157.03  4983.9  152.35  4988.4  150.84  4990.3   150.7  4992.5  150.18
  4992.6  150.16  4999.1  149.24  5000.6  149.39  5008.8  150.22  5009.7  150.77
  5012.3   151.1  5038.6  154.48  5042.2   154.6  5081.7  155.91  5082.2  155.93
  5129.3  156.31    5380  156.31    5410   155.8  5673.3   155.8  5683.2  156.89
  5703.2  157.79  5733.2  158.39  5743.2  158.49  5780.9  158.73  5800.9  158.85
  5823.2  158.99  5830.9  159.22  5853.2  159.89  5853.8  159.89  5890.9   159.8
    5894  159.79
BR D #Mann= 5
  4011.3      .2    4387     .05  4463.1     .08    4970    .055  5038.6     .07
BC Design=,, 0 ,, 0 ,,,,,,
BC HTab HWMax=166.04

Type RM Length L Ch R = 1 ,6160.1  ,260,186.7,80
BEGIN DESCRIPTION:
Downstream Section of Golf Cart Bridge 600-ft D.S. of Tomball Country Club Road
END DESCRIPTION:
XS GIS Cut Line= 6
       3049525.1      13958284.5      3049291.15       13958054.
       3048939.6      13957647.5       3048971.2       13957518.
      3048740.55      13956957.5      3048731.21      13956734.6
#Sta/Elev= 30
  4011.3  165.54  4021.3  164.84  4041.3  160.84  4061.3  159.74  4071.3  159.44
  4125.7  159.03  4201.3  159.14    4387  158.85  4463.1  158.73  4884.1  158.12
  4906.9  158.04  4925.2  157.64  4945.2  157.84    4970  156.98  4988.4  150.79
  4999.1  149.19  5008.8  150.17  5009.7  150.72  5038.6  154.43  5082.2  155.88
  5129.3  156.26    5380  156.26    5410   155.8  5673.3   155.8  5683.2  156.84
  5703.2  157.74  5733.2  158.34  5823.2  158.94  5853.2  159.84    5894  159.74
#Mann= 5 ,-1 , 0
  4011.3      .2       0    4387     .05       0  4463.1     .08       0
    4970    .055       0  5038.6     .07       0
#XS Ineff= 2 , 0
       0    4970  155.38  5038.6       0  155.38
Permanent Ineff=
       F       F
Bank Sta=4970,5038.6
Exp/Cntr=0.5,0.3

Type RM Length L Ch R = 1 ,5973.4  ,105.41,284.6,247.01
BEGIN DESCRIPTION:
Cross Section 5973.4
Cross Section XS-07
END DESCRIPTION:
XS GIS Cut Line= 6
      3049607.31      13958188.4      3049408.36       13957951.
      3049158.38      13957525.1      3049000.98      13957441.8
      3048815.81      13956932.6      3048791.66       13956728.
#Sta/Elev= 30
  4102.4   166.2  4112.4     165  4122.4   162.4  4132.4   160.5  4152.4   159.3
  4172.4   158.8  4342.4   158.6  4412.1   159.3  4612.1   158.9  4667.1  158.35
  4742.1   157.7    4943  157.89  4946.9  157.16  4965.7  156.39  4984.1   150.2
  4994.8   148.6  5034.3  153.84  5077.9  155.29    5125  155.67  5154.1   155.1
  5214.1   158.5  5314.1   159.4  5354.1   158.3  5374.1   155.7  5404.1   153.8
  5504.1   153.2  5625.9   154.7  5725.9   156.6  5755.9   157.9  5831.9   159.9
#Mann= 6 ,-1 , 0
  4102.4      .2       0  4412.1     .05       0  4667.1     .12       0
  4965.7    .055       0  5034.3     .12       0  5625.9      .2       0
#XS Ineff= 2 , 0
       0                 5200.13       0  159.46
Permanent Ineff=
       F       F
Bank Sta=4965.7,5034.3
Exp/Cntr=0.5,0.3

Type RM Length L Ch R = 1 ,5688.8  ,28,28,28
BEGIN DESCRIPTION:
Upstream Section of Golf Cart Bridge 1100-ft D.S. of Tomball Country Club Road
END DESCRIPTION:
XS GIS Cut Line= 4
      3049601.75      13957885.3      3049233.45      13957385.3
      3049138.82      13957232.6      3048892.04      13956874.5
#Sta/Elev= 30
  4266.1  156.36  4280.8  156.49  4480.8  157.76  4580.8  157.36  4650.8  155.96
  4700.8  155.46  4750.8  156.26  4800.8  156.26  4877.9  154.63    4900  154.66
    4923  154.69  4972.7  152.62  4990.7  151.77    4996  148.87  4999.8   147.7
  5013.1  149.63    5027  152.43  5045.1  155.78  5048.9  155.64  5063.3  151.82
  5074.2  151.19  5080.3  151.86  5110.3  151.96  5177.3  153.08  5275.4  153.26
  5435.4  155.56  5455.4  156.16  5495.4  156.46  5525.4  157.56    5545  157.66
#Mann= 7 ,-1 , 0
  4266.1      .2       0  4280.8     .05       0    4900     .15       0
  4972.7    .055       0    5027     .15       0  5177.3     .05       0
    5545      .2       0
#XS Ineff= 2 ,-1
  4925.4  4990.7  154.55 5026.95  5138.3   152.5
Permanent Ineff=
       F       F
Bank Sta=4972.7,5027
Exp/Cntr=0.5,0.3

Type RM Length L Ch R = 3 ,5674.8  ,,,
BEGIN DESCRIPTION:
GOLF CART BRIDGE 1,100FT DS TOMBALL COUNTRY CLUB ROAD
Cross Section 5674.8
Structure ID: M116-00-00-08
END DESCRIPTION:
Bridge Culvert--1,0,-1,-1, 0
Deck Dist Width WeirC Skew NumUp NumDn MinLoCord MaxHiCord MaxSubmerge Is_Ogee
10,8,2.6,0, 67, 67, , , 0.95, 0, 1,1,,
  4266.1  4280.8  4370.8  4480.8  4506.1  4580.8  4596.1  4606.1  4650.8  4700.8
  4716.1  4726.1  4730.8  4746.1  4750.8  4800.8  4810.8  4816.1  4850.7  4877.9
    4900  4921.1    4923  4972.7  4981.3  4990.7    4996  4998.1  4998.8  4999.8
  5000.6  5001.8  5002.7  5007.4  5013.1    5027  5027.3 5027.49  5027.6  5027.7
  5044.2  5045.1  5048.9  5052.5  5063.3  5074.2  5080.3  5090.3  5097.2  5101.4
  5110.3  5115.4  5151.4  5165.4  5177.3  5181.4  5201.4  5241.4  5275.4  5401.4
  5455.4  5495.4  5501.4  5525.4  5531.4  5533.7    5545
  156.33  156.46  157.23  157.73  157.63  157.33  157.02  156.82  155.93  155.43
  155.58  155.68  155.73  156.11  156.23  156.23  156.13     156  155.33  154.99
  154.63  154.66  154.66  154.55  154.73   154.8  154.81  154.81  154.81  154.82
  154.82  154.82  154.82  154.79  154.76  154.68  154.68  154.72  154.74  154.75
  156.25  156.22  156.08  155.95  155.14  154.32  153.87  153.12   152.6   152.6
  152.55  152.52  152.75  153.03  153.05  153.06   153.1  153.17  153.57   155.1
  156.13  156.43  156.65  157.53  157.56  157.57  157.63
                                                                                
                                                                                
                                           152.5  152.51  152.51  152.51  152.52
  152.52  152.52  152.52  152.49  152.46  152.38
                                                                                
                                                                                
                                                        
  4266.1  4280.8  4370.8  4480.8  4506.1  4580.8  4596.1  4606.1  4650.8  4700.8
  4716.1  4726.1  4730.8  4746.1  4750.8  4800.8  4810.8  4816.1  4850.7  4877.9
    4900  4921.1    4923  4972.7  4981.3  4990.7    4996  4998.1  4998.8  4999.8
  5000.6  5001.8  5002.7  5007.4  5013.1    5027  5027.3 5027.49  5027.6  5027.7
  5044.2  5045.1  5048.9  5052.5  5063.3  5074.2  5080.3  5090.3  5097.2  5101.4
  5110.3  5115.4  5151.4  5165.4  5177.3  5181.4  5201.4  5241.4  5275.4  5401.4
  5455.4  5495.4  5501.4  5525.4  5531.4  5533.7    5545
   156.3  156.44  157.21  157.71  157.61  157.31     157   156.8  155.91  155.41
  155.56  155.66  155.71  156.09  156.21  156.21  156.11  155.98  155.31  154.99
  154.61  154.64  154.64  154.55  154.73   154.8  154.81  154.81  154.81  154.82
  154.82  154.82  154.82  154.79  154.76  154.68  154.68  154.72  154.74  154.75
  156.25  156.22  156.08  155.95  155.14  154.32  153.87  153.12   152.6   152.6
  152.55  152.52  152.73  153.01  153.03  153.04  153.08  153.15  153.57   155.1
  156.13  156.41  156.63  157.51  157.54  157.55   157.6
                                                                                
                                                                                
                                           152.5  152.51  152.51  152.51  152.52
  152.52  152.52  152.52  152.49  152.46  152.38
                                                                                
                                                                                
                                                        
BR Coef= 1 , 1 , 0 ,1.25, 0 ,,,0.8,0,2,0,
WSPro=,,,, 1 ,,,, 0 ,,,, 0 ,,,,-1 ,-1 ,-1 , 0 , 0 , 0 , 0 , 0
BR U #Sta/Elev= 75
  4266.1  156.33  4280.8  156.46  4370.8  157.23  4480.8  157.73  4506.1  157.63
  4580.8  157.33  4596.1  157.02  4606.1  156.82  4650.8  155.93  4700.8  155.43
  4716.1  155.58  4726.1  155.68  4730.8  155.73  4746.1  156.11  4750.8  156.23
  4800.8  156.23  4810.8  156.13  4816.1     156  4849.1  155.16  4850.7  155.33
  4877.9   154.6  4880.9   154.6    4900  154.63  4921.1  154.66    4923  154.66
  4972.7  152.59  4981.3  152.18  4981.4  152.18 4981.51  152.17  4981.6  152.17
  4990.7  151.74    4996  148.84  4998.1  147.97  4998.8  147.88  4999.8  147.67
  5000.6   147.8  5001.8  147.93  5002.7  148.06  5007.4  148.71  5013.1   149.6
    5027   152.4  5027.3  152.46 5027.49  152.49  5027.6  152.51  5027.7  152.53
  5044.2  155.58  5045.1  155.75  5048.9  155.61  5052.5  154.65  5063.3  151.79
  5074.2  151.16  5080.3  151.83  5090.3  151.93  5097.2  151.93  5101.4  151.93
  5110.3  151.93  5115.4  152.03  5151.4  152.75  5165.4  153.03  5177.3  153.05
  5181.4  153.06  5201.4   153.1  5241.4  153.17  5275.4  153.23  5311.4  153.75
  5401.4  155.04  5435.4  155.53  5441.4  155.71  5455.4  156.13  5495.4  156.43
  5501.4  156.65  5525.4  157.53  5531.4  157.56  5533.7  157.57    5545  157.63
BR U #Mann= 6
  4266.1      .2  4280.8     .05    4900     .15  4972.7    .045    5027     .15
  5177.3     .05
BR U Banks=4972.7,5027
BR D #Sta/Elev= 75
  4266.1  156.26  4280.8  156.39  4370.8  157.16  4480.8  157.66  4506.1  157.56
  4580.8  157.26  4596.1  156.95  4606.1  156.75  4650.8  155.86  4700.8  155.36
  4716.1  155.51  4726.1  155.61  4730.8  155.66  4746.1  156.04  4750.8  156.16
  4800.8  156.16  4810.8  156.06  4816.1  155.93  4849.1  155.09  4850.7  155.26
  4877.9  154.53  4880.9  154.53    4900  154.56  4921.1  154.59    4923  154.59
  4972.7  152.52  4981.3  152.11  4981.4  152.11 4981.51   152.1  4981.6   152.1
  4990.7  151.67    4996  148.77  4998.1   147.9  4998.8  147.81  4999.8   147.6
  5000.6  147.73  5001.8  147.86  5002.7  147.99  5007.4  148.64  5013.1  149.53
    5027  152.33  5027.3  152.39 5027.49  152.42  5027.6  152.44  5027.7  152.46
  5044.2  155.51  5045.1  155.68  5048.9  155.54  5052.5  154.58  5063.3  151.72
  5074.2  151.09  5080.3  151.76  5090.3  151.86  5097.2  151.86  5101.4  151.86
  5110.3  151.86  5115.4  151.96  5151.4  152.68  5165.4  152.96  5177.3  152.98
  5181.4  152.99  5201.4  153.03  5241.4   153.1  5275.4  153.16  5311.4  153.68
  5401.4  154.97  5435.4  155.46  5441.4  155.64  5455.4  156.06  5495.4  156.36
  5501.4  156.58  5525.4  157.46  5531.4  157.49  5533.7   157.5    5545  157.56
BR D #Mann= 6
  4266.1      .2  4280.8     .05    4900     .15  4972.7    .045    5027     .15
  5177.3     .05
BR D Banks=4972.7,5027
BC Design=,, 0 ,, 0 ,,,,,,
BC HTab HWMax=157.76