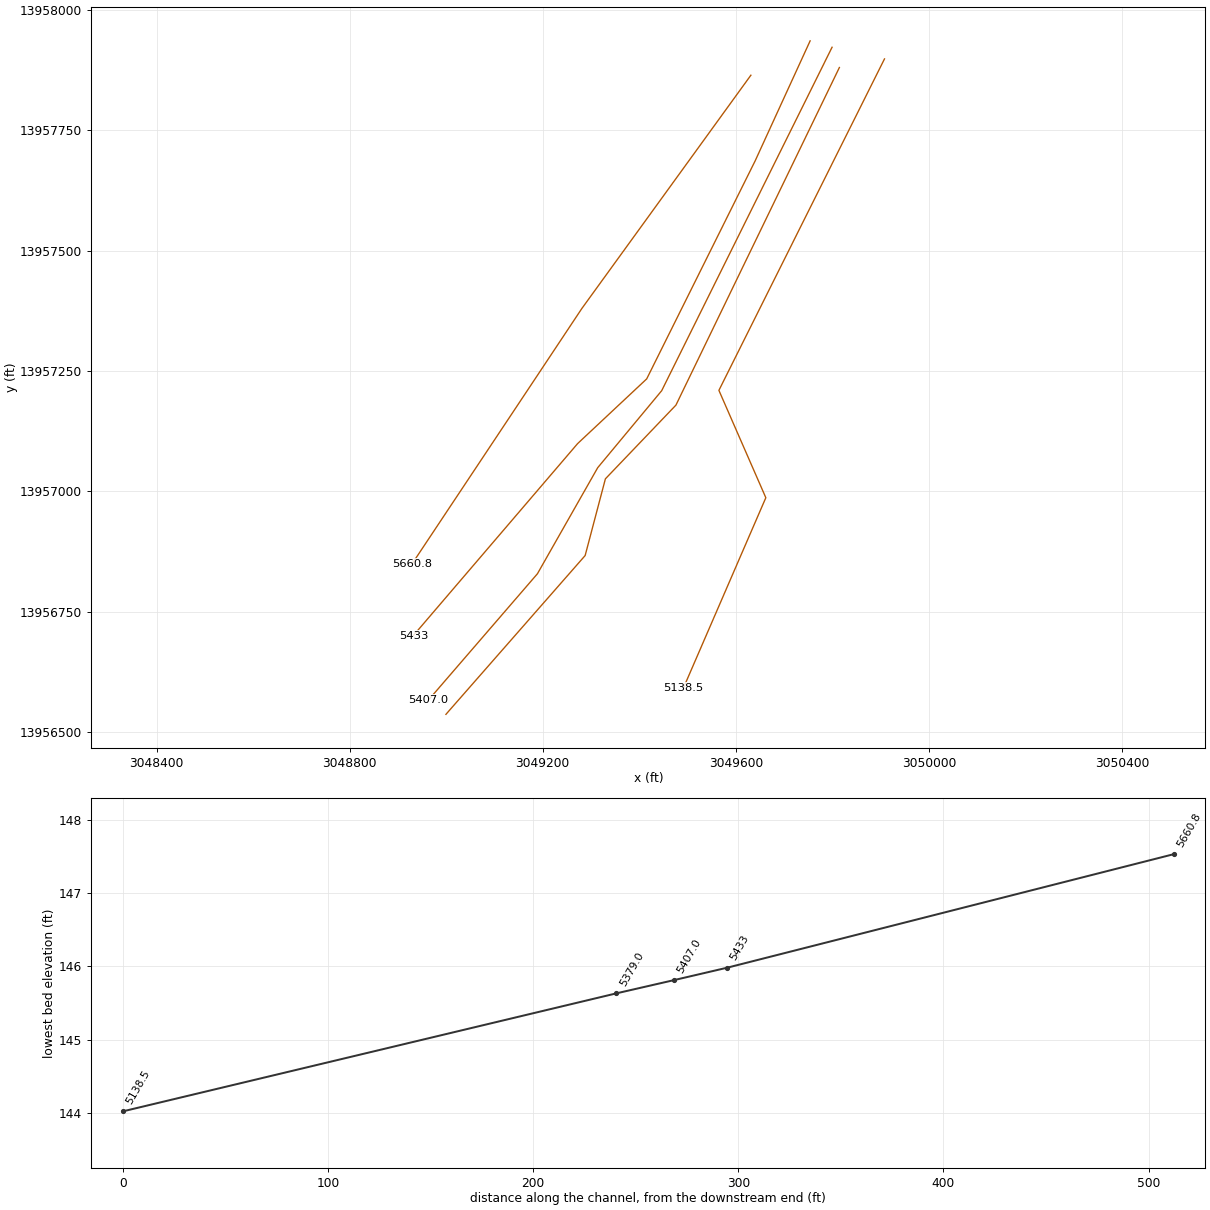
HEC-RAS study M116-00-00.PRJ: M116-00-00

--- M116-00-00.g01 (geometry) --- (continued)

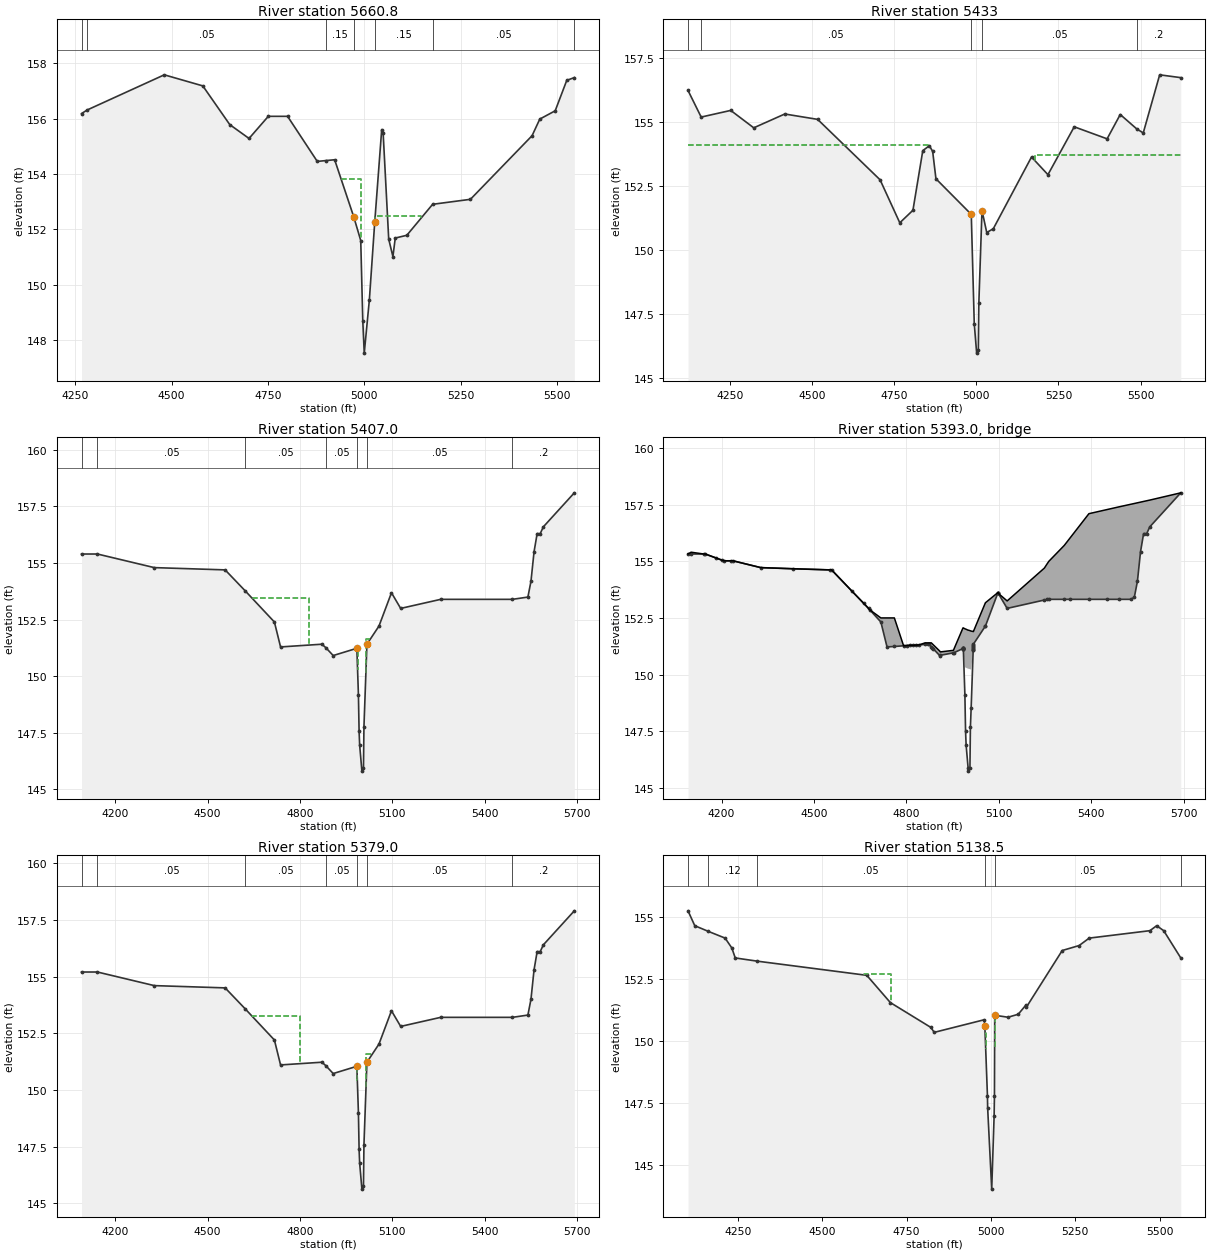
Type RM Length L Ch R = 1 ,5660.8  ,217.8,217.8,217.8
BEGIN DESCRIPTION:
Downstream Section of Golf Cart Bridge 1100-ft D.S. of Tomball Country Club Road
END DESCRIPTION:
XS GIS Cut Line= 4
      3049631.32      13957863.8      3049281.26      13957379.9
      3049168.94      13957210.6      3048929.68      13956850.3
#Sta/Elev= 30
  4266.1  156.19  4280.8  156.32  4480.8  157.59  4580.8  157.19  4650.8  155.79
  4700.8  155.29  4750.8  156.09  4800.8  156.09  4877.9  154.46    4900  154.49
    4923  154.52  4972.7  152.45  4990.7   151.6    4996   148.7  4999.8  147.53
  5013.1  149.46    5027  152.26  5045.1  155.61  5048.9  155.47  5063.3  151.65
  5074.2  151.02  5080.3  151.69  5110.3  151.79  5177.3  152.91  5275.4  153.09
  5435.4  155.39  5455.4  155.99  5495.4  156.29  5525.4  157.39    5545  157.49
#Mann= 7 ,-1 , 0
  4266.1      .2       0  4280.8     .05       0    4900     .15       0
  4972.7    .055       0    5027     .15       0  5177.3     .05       0
    5545      .2       0
#XS Ineff= 2 ,-1
  4939.5 4990.56  153.82    5027 5146.65   152.5
Permanent Ineff=
       F       F
Bank Sta=4972.7,5027
Exp/Cntr=0.5,0.3

Type RM Length L Ch R = 1 ,5433    ,26,26,26
BEGIN DESCRIPTION:
Cross Section XS06.75
END DESCRIPTION:
XS GIS Cut Line= 5
      3049754.11      13957935.1      3049639.97     13957685.56
       3049415.5     13957233.62      3049272.42      13957099.4
      3048931.94      13956700.9
#Sta/Elev= 30
    4123  156.24    4163   155.2    4253  155.46    4323  154.78  4417.4  155.32
  4517.4  155.11  4707.4  152.75  4767.4  151.07  4807.4  151.56  4837.4  153.89
  4857.4  154.08  4867.4  153.86  4877.4  152.79  4984.9   151.4    4994  147.13
  5001.3  145.98  5006.4  146.12  5007.9  147.92 5017.51  151.55    5032  150.69
    5052  150.84  5168.2  153.64  5218.2  152.95  5298.2  154.82  5398.2  154.35
  5438.2   155.3  5488.2  154.74  5508.2  154.58  5558.2  156.85  5622.4  156.74
#Mann= 5 ,-1 , 0
    4123     .12       0    4163     .05       0  4984.9    .035       0
 5017.51     .05       0  5488.2      .2       0
#XS Ineff= 2 , 0
         4852.52   154.1 5178.18           153.7
Permanent Ineff=
       F       F
Bank Sta=4984.9,5017.51
Exp/Cntr=0.5,0.3

Type RM Length L Ch R = 1 ,5407.0  ,28,28,28
BEGIN DESCRIPTION:
Upstream Section of Golf Cart Bridge 1400-ft D.S. of Tomball Country Club Road
END DESCRIPTION:
XS GIS Cut Line= 5
    3049799.5521   13957921.8239      3049446.53      13957209.1
      3049313.97      13957049.3      3049189.06      13956829.2
    3048963.5685   13956567.4706
#Sta/Elev= 30
    4091  155.39  4142.5  155.39  4327.2  154.79  4557.2  154.69  4622.7  153.76
  4717.2  152.39  4737.2  151.29  4871.3  151.41    4884  151.26  4908.1  150.91
  4984.9  151.23    4990  149.18  4992.2  147.56    4994  146.96  5001.3  145.81
  5006.4  145.95  5007.9  147.75  5017.6  151.41  5056.7  152.21  5097.3  153.68
  5127.2  152.99  5257.2  153.39  5489.9  153.39  5540.3  153.49  5550.3  154.19
  5560.3  155.49  5570.3  156.29  5580.3  156.29  5590.5  156.59    5691  158.09
#Mann= 7 ,-1 , 0
    4091     .12       0  4142.5     .05       0  4622.7     .05       0
    4884     .05       0  4984.9    .035       0  5017.6     .05       0
  5489.9      .2       0
#XS Ineff= 3 ,-1
 4646.91 4831.02  153.45 4985.34 4987.23  151.06 5014.22  5028.3  151.65
Permanent Ineff=
       F       F       F
Bank Sta=4984.9,5017.6
Exp/Cntr=0.5,0.3

Type RM Length L Ch R = 3 ,5393.0  ,,,
BEGIN DESCRIPTION:
GOLF CART BRIDGE 1,400FT DS TOMBALL COUNTRY CLUB RD
Cross Section 5393.0
Structure ID: M116-00-00-07
END DESCRIPTION:
Bridge Culvert--1,0,-1,-1, 0
Deck Dist Width WeirC Skew NumUp NumDn MinLoCord MaxHiCord MaxSubmerge Is_Ogee
10,8,2.6,0, 78, 78, , , 0.95, 0, 1,1,,
    4091    4101  4142.5  4147.2    4181    4201  4207.2    4231  4237.2  4327.2
    4431    4551  4557.2  4622.7    4661  4677.2    4681  4717.2  4737.2    4761
    4791    4801    4811    4821    4831    4841    4861  4871.3  4873.9    4881
  4908.1  4910.2  4952.8    4954  4983.8 4983.91 4983.99  4984.1  4984.2  4984.3
 4984.41  4984.9    4990  4992.2    4994  5000.3  5001.3  5006.4  5007.9  5010.3
  5016.9 5016.99  5017.1 5017.19  5017.3  5017.4 5017.51  5017.6  5056.6  5056.7
  5097.3  5097.9  5098.1  5127.2  5248.1  5257.2  5262.7  5312.7  5392.7  5489.9
  5530.3  5540.3  5550.3  5560.3  5570.3  5580.3  5590.5    5691
  155.32   155.4  155.32  155.32  155.15  155.05  155.02  155.02  155.02  154.72
  154.67  154.62  154.62  153.69  153.15  152.92  152.86   152.5   152.5   152.5
  151.27  151.28  151.29  151.29   151.3  151.31   151.4   151.4   151.4   151.4
  151.04     151  151.07  151.11  152.06  152.06  152.06  152.06  152.06  152.06
  152.06  152.06  152.02  152.01     152  151.96  151.96  151.94  151.93  151.92
   151.9   151.9   151.9   151.9   151.9   151.9   151.9   151.9  153.17  153.17
  153.62  153.63  153.59  153.25   154.7  154.89     155   155.7   157.1   157.4
  157.52  157.55  157.58  157.61  157.64  157.67   157.7  158.02
                                                                                
                                                                                
                                                                                
                                                                                
  150.36  150.36  150.32  150.31   150.3  150.26  150.26  150.24  150.23  150.22
   150.2   150.2   150.2   150.2   150.2   150.2   150.2
                                                                                
                                                                
    4091    4101  4142.5  4147.2    4181    4201  4207.2    4231  4237.2  4327.2
    4431    4551  4557.2  4622.7    4661  4677.2    4681  4717.2  4737.2    4761
    4791    4801    4811    4821    4831    4841    4861  4871.3  4873.9    4881
  4908.1  4910.2  4952.8    4954  4983.8 4983.91 4983.99  4984.1  4984.2  4984.3
 4984.41  4984.9    4990  4992.2    4994  5000.3  5001.3  5006.4  5007.9  5010.3
  5016.9 5016.99  5017.1 5017.19  5017.3  5017.4 5017.51  5017.6  5056.6  5056.7
  5097.3  5097.9  5098.1  5127.2  5248.1  5257.2  5262.7  5312.7  5392.7  5489.9
  5530.3  5540.3  5550.3  5560.3  5570.3  5580.3  5590.5    5691
   155.3   155.4  155.31  155.31  155.14  155.04  155.01  155.01  155.01  154.71
  154.66  154.61  154.61  153.68  153.14  152.91  152.85   152.5   152.5   152.5
  151.26  151.27  151.28  151.28  151.29   151.3   151.4   151.4   151.4   151.4
  151.04     151  151.07  151.11  152.06  152.06  152.06  152.06  152.06  152.06
  152.06  152.06  152.02  152.01     152  151.96  151.96  151.94  151.93  151.92
   151.9   151.9   151.9   151.9   151.9   151.9   151.9   151.9  153.17  153.17
  153.62  153.63  153.58  153.25   154.7  154.89     155   155.7   157.1   157.4
  157.52  157.55  157.58  157.61  157.64  157.67   157.7     158
                                                                                
                                                                                
                                                                                
                                                                                
  150.36  150.36  150.32  150.31   150.3  150.26  150.26  150.24  150.23  150.22
   150.2   150.2   150.2   150.2   150.2   150.2   150.2
                                                                                
                                                                
BR Coef= 1 , 1 , 0 ,1.25, 0 ,,,0.8,0,2,0,
WSPro=,,,, 1 ,,,, 0 ,,,, 0 ,,,,-1 ,-1 ,-1 , 0 , 0 , 0 , 0 , 0
BR U #Sta/Elev= 82
    4091  155.32    4101  155.32  4142.5  155.32  4147.2  155.32    4181  155.15
    4201  155.05  4207.2  155.02    4231  155.02  4237.2  155.02  4327.2  154.72
    4431  154.67    4551  154.62  4557.2  154.62  4622.7  153.69    4661  153.15
  4677.2  152.92    4681  152.86  4717.2  152.32  4737.2  151.22    4761  151.24
    4791  151.27    4801  151.28    4811  151.29    4821  151.29    4831   151.3
    4841  151.31    4861  151.33  4871.3  151.34  4873.9  151.33    4881  151.23
    4884  151.19  4886.5  151.15  4908.1  150.84  4910.2  150.85  4952.8  150.96
    4954  150.96  4983.8  151.15 4983.91  151.15 4983.99  151.15  4984.1  151.15
  4984.2  151.16  4984.3  151.16 4984.41  151.16  4984.9  151.16    4990  149.11
  4992.2  147.49    4994  146.89  5000.3   145.9  5001.3  145.74  5006.4  145.88
  5007.9  147.68  5010.3  148.51  5016.9  151.07 5016.99   151.1  5017.1  151.15
 5017.19  151.18  5017.3  151.22  5017.4  151.26 5017.51  151.31  5017.6  151.34
  5056.6  152.14  5056.7  152.14  5097.3  153.61  5097.9   153.6  5098.1  153.59
  5127.2  152.92  5248.1  153.29  5257.2  153.32  5262.7  153.32  5312.7  153.32
  5332.7  153.32  5392.7  153.32  5452.7  153.32  5489.9  153.32  5530.3  153.32
  5540.3  153.42  5550.3  154.12  5560.3  155.42  5570.3  156.22  5580.3  156.22
  5590.5  156.52    5691  158.02
BR U #Mann= 7
    4091     .12  4142.5     .05  4622.7     .05    4884     .05  4984.9     .03
  5017.6     .05  5489.9      .2
BR U Banks=4984.9,5017.6
BR D #Sta/Elev= 82
    4091  155.28    4101  155.28  4142.5  155.28  4147.2  155.28    4181  155.11
    4201  155.01  4207.2  154.98    4231  154.98  4237.2  154.98  4327.2  154.68
    4431  154.63    4551  154.58  4557.2  154.58  4622.7  153.65    4661  153.11
  4677.2  152.88    4681  152.82  4717.2  152.28  4737.2  151.18    4761   151.2
    4791  151.23    4801  151.24    4811  151.25    4821  151.25    4831  151.26
    4841  151.27    4861  151.29  4871.3   151.3  4873.9  151.29    4881  151.19
    4884  151.15  4886.5  151.11  4908.1   150.8  4910.2  150.81  4952.8  150.92
    4954  150.92  4983.8  151.11 4983.91  151.11 4983.99  151.11  4984.1  151.11
  4984.2  151.12  4984.3  151.12 4984.41  151.12  4984.9  151.12    4990  149.07
  4992.2  147.45    4994  146.85  5000.3  145.86  5001.3   145.7  5006.4  145.84
  5007.9  147.64  5010.3  148.47  5016.9  151.03 5016.99  151.06  5017.1  151.11
 5017.19  151.14  5017.3  151.18  5017.4  151.22 5017.51  151.27  5017.6   151.3
  5056.6   152.1  5056.7   152.1  5097.3  153.57  5097.9  153.56  5098.1  153.55
  5127.2  152.88  5248.1  153.25  5257.2  153.28  5262.7  153.28  5312.7  153.28
  5332.7  153.28  5392.7  153.28  5452.7  153.28  5489.9  153.28  5530.3  153.28
  5540.3  153.38  5550.3  154.08  5560.3  155.38  5570.3  156.18  5580.3  156.18
  5590.5  156.48    5691  157.98
BR D #Mann= 7
    4091     .12  4142.5     .05  4622.7     .05    4884     .05  4984.9     .03
  5017.6     .05  5489.9      .2
BR D Banks=4984.9,5017.6
BC Design=,, 0 ,, 0 ,,,,,,
BC HTab HWMax=158.09

Type RM Length L Ch R = 1 ,5379.0  ,240.5,240.5,240.5
BEGIN DESCRIPTION:
Downstream Section of Golf Cart Bridge 1400-ft D.S. of Tomball Country Club Road
END DESCRIPTION:
XS GIS Cut Line= 5
    3049814.7142   13957879.7878      3049476.07      13957179.2
      3049329.91      13957026.2      3049287.95       13956867.
    3048999.5248    13956537.507
#Sta/Elev= 30
    4091  155.21  4142.5  155.21  4327.2  154.61  4557.2  154.51  4622.7  153.58
  4717.2  152.21  4737.2  151.11  4871.3  151.23    4884  151.08  4908.1  150.73
  4984.9  151.05    4990     149  4992.2  147.38    4994  146.78  5001.3  145.63
  5006.4  145.77  5007.9  147.57  5017.6  151.23  5056.7  152.03  5097.3   153.5
  5127.2  152.81  5257.2  153.21  5489.9  153.21  5540.3  153.31  5550.3  154.01
  5560.3  155.31  5570.3  156.11  5580.3  156.11  5590.5  156.41    5691  157.91
#Mann= 7 ,-1 , 0
    4091     .12       0  4142.5     .05       0  4622.7     .05       0
    4884     .05       0  4984.9    .035       0  5017.6     .05       0
  5489.9      .2       0
#XS Ineff= 3 ,-1
 4645.96 4801.48  153.26 4984.96 4986.73  151.02 5014.71 5035.63   151.6
Permanent Ineff=
       F       F       F
Bank Sta=4984.9,5017.6
Exp/Cntr=0.5,0.3

Type RM Length L Ch R = 1 ,5138.5  ,27,27,27
BEGIN DESCRIPTION:
Upstream Section of Golf Cart Bridge 1650-ft D.S. of Tomball Country Club Road
END DESCRIPTION:
XS GIS Cut Line= 4
      3049908.14      13957897.6      3049565.09      13957209.8
      3049662.32       13956987.      3049491.82      13956592.7
#Sta/Elev= 30
  4101.8  155.24  4121.8  154.64  4162.3  154.41  4211.8  154.14  4231.8  153.74
  4241.8  153.34  4307.6  153.21  4631.8  152.64  4701.8  151.54  4821.8  150.54
  4831.8  150.34  4980.5  150.85  4981.9   150.6  4989.7  147.76  4990.2  147.31
  5002.3  144.02  5009.4  146.96  5010.4  147.76  5011.2  151.03  5050.6  150.95
    5081  151.07  5104.2  151.45  5104.8  151.35  5211.4  153.64  5261.4  153.84
  5291.4  154.14  5471.4  154.44  5491.4  154.64  5512.3  154.44  5562.9  153.34
#Mann= 6 ,-1 , 0
  4101.8      .2       0  4162.3     .12       0  4307.6     .05       0
  4981.9    .035       0  5011.2     .05       0  5562.9      .2       0
#XS Ineff= 3 ,-1
  4622.7 4702.31  152.69 4982.59 4984.41  150.33 5010.89 5011.17   150.9
Permanent Ineff=
       F       F       F
Bank Sta=4981.9,5011.2
Exp/Cntr=0.5,0.3