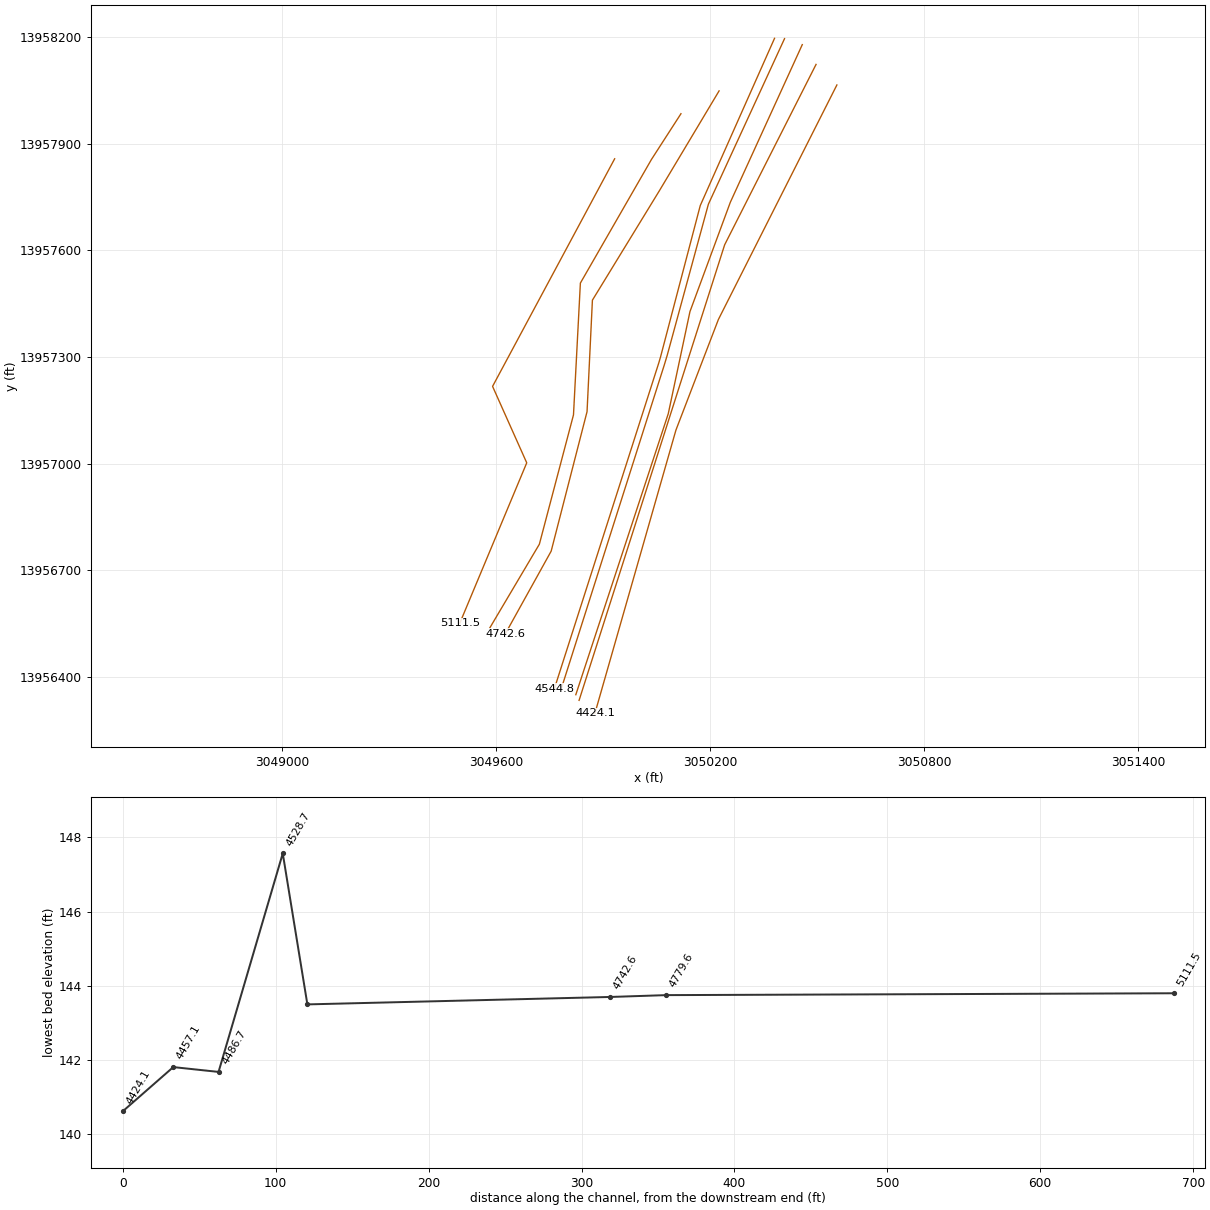
HEC-RAS study M116-00-00.PRJ: M116-00-00

--- M116-00-00.g01 (geometry) --- (continued)

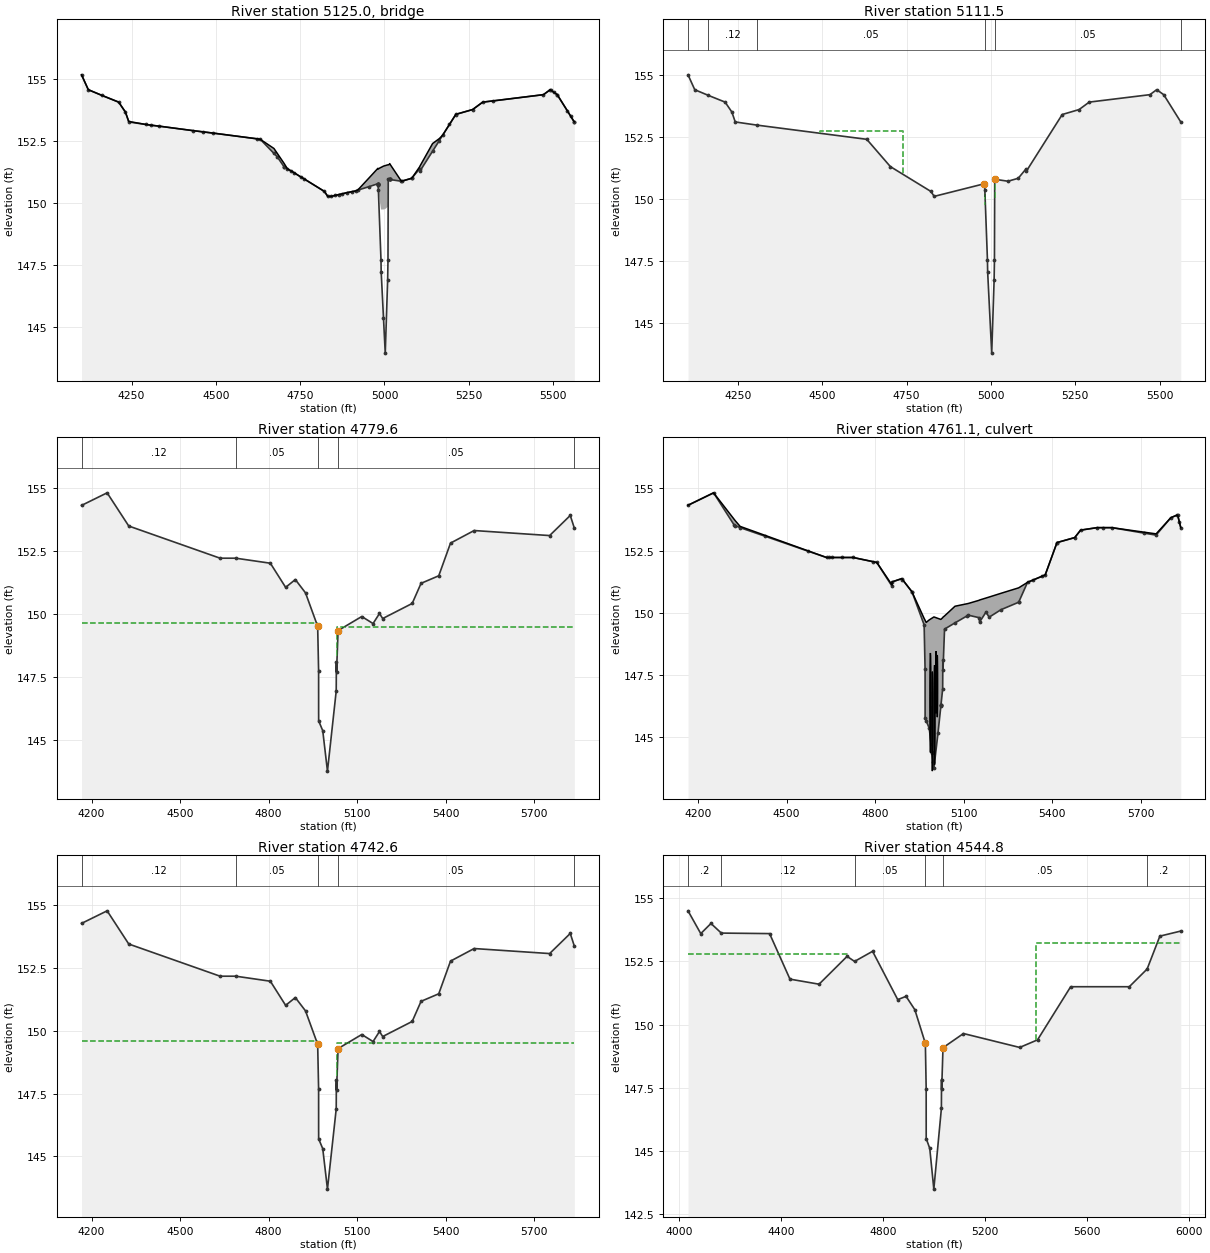
Type RM Length L Ch R = 3 ,5125.0  ,,,
BEGIN DESCRIPTION:
GOLF CART BRIDGE 1,650FT DS TOMBALL COUNTRY CLUB RD
Cross Section 5125.0
Structure ID: M116-00-00-06
END DESCRIPTION:
Bridge Culvert--1,0,-1,-1, 0
Deck Dist Width WeirC Skew NumUp NumDn MinLoCord MaxHiCord MaxSubmerge Is_Ogee
10,7,2.6,0, 79, 79, , , 0.95, 0, 1,1,,
  4101.8  4121.8  4162.3  4211.8  4231.8  4241.8  4291.8  4307.6  4332.3  4432.3
  4462.3  4492.3  4622.3  4631.8  4672.3  4681.8  4701.8  4702.3  4712.3  4722.3
  4732.3  4752.3  4762.3  4821.8  4831.8  4841.8  4854.1  4864.1  4874.1    4889
  4904.1  4914.8  4920.5    4954  4980.5  4980.6  4980.7  4980.8 4980.91    4981
  4981.1  4981.9  4989.7  4990.2  4997.1  5002.3  5009.4  5010.4  5011.2  5014.9
 5014.99  5015.1  5015.2  5015.3  5050.2  5050.6    5081  5081.4  5104.2  5104.8
  5142.7  5162.7  5172.7  5192.7  5211.4  5212.7  5261.4  5291.4  5322.7  5471.4
  5491.4  5492.7  5502.7  5512.3  5512.7  5542.7  5552.7  5562.7  5562.9
  155.17  154.57  154.34  154.07  153.67  153.29  153.17  153.14   153.1  152.92
  152.87  152.82  152.59  152.57   152.2  152.01  151.61   151.6  151.38   151.3
  151.22  151.05  150.97  150.47  150.27  150.27  150.31  150.34  150.37  150.42
  150.46  150.49  150.52  151.01   151.4  151.39  151.37  151.37  151.37  151.37
  151.37  151.38  151.44  151.44  151.49  151.51  151.54  151.54  151.54  151.56
  151.56  151.56  151.58  151.59  150.88  150.88     151  151.01  151.46  151.48
   152.4   152.6  152.74  153.17  153.57  153.58  153.77  154.07  154.12  154.37
  154.57  154.56  154.46  154.37  154.36  153.71  153.49  153.27  153.27
                                                                                
                                                                                
                                                                                
                                                                  149.67  149.67
  149.67  149.68  149.74  149.74  149.74  149.76  149.84  149.84  149.84
                                                                                
                                                                                
                                                                        
  4101.8  4121.8  4162.3  4211.8  4231.8  4241.8  4291.8  4307.6  4332.3  4432.3
  4462.3  4492.3  4622.3  4631.8  4672.3  4681.8  4701.8  4702.3  4712.3  4722.3
  4732.3  4752.3  4762.3  4821.8  4831.8  4841.8  4854.1  4864.1  4874.1    4889
  4904.1  4914.8  4920.5    4954  4980.5  4980.6  4980.7  4980.8 4980.91    4981
  4981.1  4981.9  4989.7  4990.2  4997.1  5002.3  5009.4  5010.4  5011.2  5014.9
 5014.99  5015.1  5015.2  5015.3  5050.2  5050.6    5081  5081.4  5104.2  5104.8
  5142.7  5162.7  5172.7  5192.7  5211.4  5212.7  5261.4  5291.4  5322.7  5471.4
  5491.4  5492.7  5502.7  5512.3  5512.7  5542.7  5552.7  5562.7  5562.9
   155.1   154.5  154.28  154.01  153.61  153.29  153.11  153.08  153.04  152.86
  152.81  152.76  152.53  152.51   152.2  152.01  151.61   151.6  151.32  151.24
  151.16  150.99  150.91  150.41  150.21  150.21  150.25  150.28  150.31  150.36
   150.4  150.43  150.46  151.01   151.4  151.39  151.37  151.37  151.37  151.37
  151.37  151.38  151.44  151.44  151.49  151.51  151.54  151.54  151.54  151.56
  151.56  151.56  151.58  151.59  150.85  150.84  150.94  150.95  151.46  151.48
   152.4   152.6  152.68  153.11  153.51  153.52  153.71  154.01   154.1  154.31
  154.51   154.5   154.4  154.31   154.3  153.65  153.43   153.2   153.2
                                                                                
                                                                                
                                                                                
                                                                  149.67  149.67
  149.67  149.68  149.74  149.74  149.74  149.76  149.84  149.84  149.84
                                                                                
                                                                                
                                                                        
BR Coef= 1 , 1 , 0 ,1.25, 0 ,,,0.8,0,2,0,
WSPro=,,,, 1 ,,,, 0 ,,,, 0 ,,,,-1 ,-1 ,-1 , 0 , 0 , 0 , 0 , 0
BR U #Sta/Elev= 79
  4101.8  155.17  4121.8  154.57  4162.3  154.34  4211.8  154.07  4231.8  153.67
  4241.8  153.27  4291.8  153.17  4307.6  153.14  4332.3   153.1  4432.3  152.92
  4462.3  152.87  4492.3  152.82  4622.3  152.59  4631.8  152.57  4672.3     152
  4681.8  151.87  4701.8  151.47  4702.3  151.47  4712.3  151.38  4722.3   151.3
  4732.3  151.22  4752.3  151.05  4762.3  150.97  4821.8  150.47  4831.8  150.27
  4841.8  150.27  4854.1  150.31  4864.1  150.34  4874.1  150.37    4889  150.42
  4904.1  150.46  4914.8  150.49  4920.5  150.52    4954  150.66  4980.5  150.78
  4980.6  150.78  4980.7  150.78  4980.8  150.78 4980.91  150.75    4981  150.73
  4981.1  150.71  4981.9  150.53  4989.7  147.69  4990.2  147.24  4997.1  145.36
  5002.3  143.95  5009.4  146.89  5010.4  147.69  5011.2  150.96  5014.9  150.95
 5014.99  150.95  5015.1  150.95  5015.2  150.95  5015.3  150.95  5050.2  150.88
  5050.6  150.88    5081     151  5081.4  151.01  5104.2  151.38  5104.8  151.28
  5142.7  152.09  5162.7  152.52  5172.7  152.74  5192.7  153.17  5211.4  153.57
  5212.7  153.58  5261.4  153.77  5291.4  154.07  5322.7  154.12  5471.4  154.37
  5491.4  154.57  5492.7  154.56  5502.7  154.46  5512.3  154.37  5512.7  154.36
  5542.7  153.71  5552.7  153.49  5562.7  153.27  5562.9  153.27
BR U #Mann= 5
  4101.8      .2  4162.3     .12  4307.6     .05  4981.9     .03  5011.2     .05
BR U Banks=4981.9,5011.2
BR D #Sta/Elev= 79
  4101.8  155.02  4121.8  154.42  4162.3  154.19  4211.8  153.92  4231.8  153.52
  4241.8  153.12  4291.8  153.02  4307.6  152.99  4332.3  152.95  4432.3  152.77
  4462.3  152.72  4492.3  152.67  4622.3  152.44  4631.8  152.42  4672.3  151.85
  4681.8  151.72  4701.8  151.32  4702.3  151.32  4712.3  151.23  4722.3  151.15
  4732.3  151.07  4752.3   150.9  4762.3  150.82  4821.8  150.32  4831.8  150.12
  4841.8  150.12  4854.1  150.16  4864.1  150.19  4874.1  150.22    4889  150.27
  4904.1  150.31  4914.8  150.34  4920.5  150.37    4954  150.51  4980.5  150.63
  4980.6  150.63  4980.7  150.63  4980.8  150.63 4980.91   150.6    4981  150.58
  4981.1  150.56  4981.9  150.38  4989.7  147.54  4990.2  147.09  4997.1  145.21
  5002.3   143.8  5009.4  146.74  5010.4  147.54  5011.2  150.81  5014.9   150.8
 5014.99   150.8  5015.1   150.8  5015.2   150.8  5015.3   150.8  5050.2  150.73
  5050.6  150.73    5081  150.85  5081.4  150.86  5104.2  151.23  5104.8  151.13
  5142.7  151.94  5162.7  152.37  5172.7  152.59  5192.7  153.02  5211.4  153.42
  5212.7  153.43  5261.4  153.62  5291.4  153.92  5322.7  153.97  5471.4  154.22
  5491.4  154.42  5492.7  154.41  5502.7  154.31  5512.3  154.22  5512.7  154.21
  5542.7  153.56  5552.7  153.34  5562.7  153.12  5562.9  153.12
BR D #Mann= 5
  4101.8      .2  4162.3     .12  4307.6     .05  4981.9     .03  5011.2     .05
BR D Banks=4981.9,5011.2
BC Design=,, 0 ,, 0 ,,,,,,
BC HTab HWMax=155.24

Type RM Length L Ch R = 1 ,5111.5  ,331.9,331.9,331.9
BEGIN DESCRIPTION:
Downstream Section of Golf Cart Bridge 1650-ft D.S. of Tomball Country Club Road
END DESCRIPTION:
XS GIS Cut Line= 4
      3049932.19      13957857.1      3049589.79      13957217.4
      3049685.61      13957002.5      3049497.98      13956552.1
#Sta/Elev= 30
  4101.8  155.02  4121.8  154.42  4162.3  154.19  4211.8  153.92  4231.8  153.52
  4241.8  153.12  4307.6  152.99  4631.8  152.42  4701.8  151.32  4821.8  150.32
  4831.8  150.12  4980.8  150.63  4981.9  150.38  4989.7  147.54  4990.2  147.09
  5002.3   143.8  5009.4  146.74  5010.4  147.54  5011.2  150.81  5050.6  150.73
    5081  150.85  5104.2  151.23  5104.8  151.13  5211.4  153.42  5261.4  153.62
  5291.4  153.92  5471.4  154.22  5491.4  154.42  5512.3  154.22  5562.9  153.12
#Mann= 6 ,-1 , 0
  4101.8      .2       0  4162.3     .12       0  4307.6     .05       0
  4981.9    .035       0  5011.2     .05       0  5562.9      .2       0
#XS Ineff= 3 ,-1
 4492.01 4740.44  152.75  4982.3 4983.54  150.22 5011.02 5011.18  150.73
Permanent Ineff=
       F       F       F
Bank Sta=4980.8,5011.2
Exp/Cntr=0.5,0.3

Type RM Length L Ch R = 1 ,4779.6  ,37,37,37
BEGIN DESCRIPTION:
Upstream Section of Golf Cart Culvert 2000-ft D.S. of Tomball Country Club Road
END DESCRIPTION:
XS GIS Cut Line= 6
      3050118.12      13957983.7      3050035.33      13957855.1
      3049836.05      13957507.7      3049816.73      13957137.3
      3049721.05      13956773.8      3049582.07      13956538.6
#Sta/Elev= 30
  4165.9  154.32  4252.6  154.82  4325.9   153.5  4635.5  152.22  4688.6  152.22
    4806  152.02  4857.8  151.06  4890.7  151.37  4925.2  150.84  4966.4  149.51
  4969.6  147.72  4969.7  145.75  4983.6  145.36  4999.6  143.75  5029.3  146.94
  5029.8  148.08  5030.4  147.69  5035.6  149.34  5115.9   149.9  5154.2  149.62
    5176  150.02  5186.9  149.82  5286.9  150.42  5316.9  151.22  5376.9  151.52
  5416.8  152.82  5496.9  153.32  5752.8  153.12  5822.8  153.92  5836.5  153.42
#Mann= 5 ,-1 , 0
  4165.9     .12       0  4688.6     .05       0  4966.4    .035       0
  5035.6     .05       0  5836.5      .2       0
#XS Ineff= 2 , 0
       0 4965.27  149.65 5032.46       0  149.49
Permanent Ineff=
       F       F
Bank Sta=4966.4,5035.6
Exp/Cntr=0.5,0.3

Type RM Length L Ch R = 2 ,4761.1  ,,,
BEGIN DESCRIPTION:
GOLF CART BRIDGE 2,000FT DS TOMBALL COUNTRY CLUB RD
Cross Section 4761.1
Structure ID: M116-00-00-05
END DESCRIPTION:
Bridge Culvert--1,0,-1,-1, 0
Deck Dist Width WeirC Skew NumUp NumDn MinLoCord MaxHiCord MaxSubmerge Is_Ogee
10,17,3,0, 43, 45, , , 0.95, 0, 1,1,,
  4165.9  4252.6  4325.9  4342.6  4635.5  4725.5    4806  4857.8    4858  4890.7
  4925.2  4966.4  4969.6  4969.7  4973.4  4983.6  4999.6  5013.5    5023  5029.3
  5029.8  5030.4  5035.6    5071  5115.9    5153  5154.2    5176  5186.9  5226.9
  5286.9  5316.9  5376.9  5416.8  5476.9  5496.9  5552.8  5602.8  5752.8  5802.8
  5822.8    5826  5836.5
  154.32  154.82   153.7  153.47  152.22  152.22  152.02  151.11  151.24  151.37
  150.84  149.77   149.7  149.69  149.61  149.71  149.83  149.77  149.73   149.8
  149.81  149.82  149.87  150.26  150.37   150.5  150.51  150.59  150.63  150.78
     151  151.22  151.52  152.82  153.02  153.32  153.42  153.42  153.17  153.82
  153.92  153.92  153.42
  154.32  154.82   153.5  153.42  152.22  152.22  152.02  151.06  151.24  151.37
  150.84  149.51  147.72  145.75  145.65  145.36  143.75  145.17  146.23  146.94
  148.08  147.69  149.34  149.59   149.9   149.8  149.62  150.02  149.82  150.12
  150.42  151.22  151.52  152.82  153.02  153.32  153.42  153.42  153.12  153.82
  153.92  153.92  153.42
  4165.9  4252.6  4325.9  4342.6  4425.9  4635.5  4725.5    4806  4857.8    4858
  4890.7  4925.2  4966.4  4969.6  4969.7  4973.4  4983.6  4999.6  5013.5    5023
  5029.3  5029.8  5030.4  5035.6    5071  5115.9    5153  5154.2    5176  5186.9
  5226.9  5286.9  5316.9  5376.9  5416.8  5476.9  5496.9  5552.8  5602.8  5711.7
  5752.8  5802.8  5822.8    5826  5836.5
   154.2  154.71   153.7  153.47  152.97  152.11  152.11  151.91  151.11  151.13
  151.26  150.73  149.77   149.7  149.69  149.61  149.71  149.83  149.77  149.73
   149.8  149.81  149.82  149.87  150.26  150.37   150.5  150.51  150.59  150.63
  150.78     151  151.12  151.41  152.71  152.91  153.21  153.31  153.31   153.1
  153.17  153.71  153.81  153.81   153.3
  154.07  154.57  153.25  153.17  152.83  151.97  151.97  151.77  150.81  150.99
  151.12  150.59  149.26  147.47   145.5   145.4  145.11   143.5  144.92  145.98
  146.69  147.83  147.44  149.09  149.34  149.65  149.55  149.37  149.77  149.57
  149.87  150.17  150.97  151.27  152.57  152.77  153.07  153.17  153.17  152.95
  152.87  153.57  153.67  153.67  153.17
BR Coef= 1 , 0 , 0 ,1.25, 0 ,,,0.8,-1,2,1,
WSPro=,,,, 1 ,,,, 0 ,,,, 0 ,,,,-1 ,-1 ,-1 , 0 , 0 , 0 , 0 , 0
Culvert=1,4,,17,0.015,0.4,1,1,3,144.38,4987.7,144.12,4987.7,Culvert #1  , 0 ,10
Culvert Bottom n=0.015
Culvert=1,4,,17,0.015,0.4,1,1,3,143.63,4994.3,143.19,4994.3,Culvert #2  , 0 ,10
Culvert Bottom n=0.015
Culvert=1,4,,17,0.015,0.4,1,1,3,143.89,5001.7,143.67,5001.7,Culvert #3  , 0 ,10
Culvert Bottom n=0.015
Culvert=1,2.5,,17,0.015,0.4,1,1,3,145.95,5006.8,145.83,5006.8,Culvert #4  , 0 ,10
Culvert Bottom n=0.015
Culvert=1,2.5,,17,0.015,0.4,1,1,3,145.8,5011.1,145.96,5011.1,Culvert #5  , 0 ,10
Culvert Bottom n=0.015
BR U #Sta/Elev= 67
  4165.9  154.32  4252.6  154.82  4322.6  153.52  4325.9   153.5  4342.6  153.42
  4425.9  153.08  4573.9  152.47  4635.5  152.22  4643.9  152.22  4653.9  152.22
  4688.6  152.22  4725.5  152.22  4793.9  152.05    4806  152.02  4857.8  151.06
    4858  151.24  4890.7  151.37    4893  151.33  4925.1  150.84  4925.2  150.84
  4966.4  149.51  4969.6  147.72  4969.7  145.75  4973.4  145.65  4983.6  145.36
 4993.19   144.4  4993.3  144.38 4993.41  144.37  4997.3  143.98  4999.6  143.75
  5013.5  145.17    5023  146.23 5023.29  146.27  5023.4  146.28 5023.51  146.29
  5029.3  146.94  5029.8  148.08  5030.4  147.69  5035.6  149.34    5071  149.59
  5111.7  149.87  5115.9   149.9    5153   149.8  5154.2  149.62    5176  150.02
  5186.9  149.82  5226.9  150.12  5286.8  150.42  5286.9  150.42  5316.9  151.22
  5336.9  151.32  5366.9  151.47  5376.9  151.52  5416.8  152.82  5416.9  152.82
  5476.9  153.02  5496.9  153.32  5552.8  153.42  5571.7  153.42  5602.8  153.42
  5711.7   153.2  5752.8  153.12  5802.8  153.82  5822.8  153.92    5826  153.92
  5831.7  153.65  5836.5  153.42
BR U #Mann= 6
  4165.9      .2  4165.9     .12  4688.6     .05  4966.4    .035  5035.6     .05
  5836.5      .2
BR U Banks=4966.4,5035.6
BR D #Sta/Elev= 67
  4165.9  154.07  4252.6  154.57  4322.6  153.27  4325.9  153.25  4342.6  153.17
  4425.9  152.83  4573.9  152.22  4635.5  151.97  4643.9  151.97  4653.9  151.97
  4688.6  151.97  4725.5  151.97  4793.9   151.8    4806  151.77  4857.8  150.81
    4858  150.99  4890.7  151.12    4893  151.08  4925.1  150.59  4925.2  150.59
  4966.4  149.26  4969.6  147.47  4969.7   145.5  4973.4   145.4  4983.6  145.11
 4993.19  144.15  4993.3  144.13 4993.41  144.12  4997.3  143.73  4999.6   143.5
  5013.5  144.92    5023  145.98 5023.29  146.02  5023.4  146.03 5023.51  146.04
  5029.3  146.69  5029.8  147.83  5030.4  147.44  5035.6  149.09    5071  149.34
  5111.7  149.62  5115.9  149.65    5153  149.55  5154.2  149.37    5176  149.77
  5186.9  149.57  5226.9  149.87  5286.8  150.17  5286.9  150.17  5316.9  150.97
  5336.9  151.07  5366.9  151.22  5376.9  151.27  5416.8  152.57  5416.9  152.57
  5476.9  152.77  5496.9  153.07  5552.8  153.17  5571.7  153.17  5602.8  153.17
  5711.7  152.95  5752.8  152.87  5802.8  153.57  5822.8  153.67    5826  153.67
  5831.7   153.4  5836.5  153.17
BR D #Mann= 6
  4165.9      .2  4165.9     .12  4688.6     .05  4966.4    .035  5035.6     .05
  5836.5      .2
BR D Banks=4966.4,5035.6
BC Design=,, 0 ,, 0 ,,,,,,
BC HTab HWMax=154.82

Type RM Length L Ch R = 1 ,4742.6  ,197.8,197.8,197.8
BEGIN DESCRIPTION:
Downstream Section of Golf Cart Culvert 2000-ft D.S. of Tomball Country Club Road
END DESCRIPTION:
XS GIS Cut Line= 6
      3050225.08      13958047.9      3050057.03      13957766.3
       3049869.8      13957459.7      3049854.75      13957146.3
      3049754.11      13956754.2      3049625.82      13956522.5
#Sta/Elev= 30
  4165.9  154.27  4252.6  154.77  4325.9  153.45  4635.5  152.17  4688.6  152.17
    4806  151.97  4857.8  151.01  4890.7  151.32  4925.2  150.79  4966.4  149.46
  4969.6  147.67  4969.7   145.7  4983.6  145.31  4999.6   143.7  5029.3  146.89
  5029.8  148.03  5030.4  147.64  5035.6  149.29  5115.9  149.85  5154.2  149.57
    5176  149.97  5186.9  149.77  5286.9  150.37  5316.9  151.17  5376.9  151.47
  5416.8  152.77  5496.9  153.27  5752.8  153.07  5822.8  153.87  5836.5  153.37
#Mann= 5 ,-1 , 0
  4165.9     .12       0  4688.6     .05       0  4966.4    .035       0
  5035.6     .05       0  5836.5      .2       0
#XS Ineff= 2 , 0
       0 4965.29  149.61 5032.15       0  149.51
Permanent Ineff=
       F       F
Bank Sta=4966.4,5035.6
Exp/Cntr=0.5,0.3

Type RM Length L Ch R = 1 ,4544.8  ,13.45,16.1,11.13
BEGIN DESCRIPTION:
Cross Section XS06.5
END DESCRIPTION:
XS GIS Cut Line= 5
      3050380.56      13958195.6      3050172.26      13957725.6
      3050061.13      13957301.1      3050055.96      13957283.4
      3049762.93      13956367.1
#Sta/Elev= 30
  4035.2   154.5  4085.2   153.6  4125.2     154  4165.9  153.62  4355.2   153.6
  4435.2   151.8  4549.3   151.6  4659.3   152.7  4688.6   152.5  4759.3   152.9
    4858  150.99  4890.7  151.12  4925.2  150.59  4966.4  149.26  4969.6  147.47
  4969.7   145.5  4983.6  145.11  4999.6   143.5  5029.3  146.69  5029.8  147.83
  5030.4  147.44  5035.6  149.09  5115.9  149.65  5336.5   149.1  5406.5   149.4
  5536.5   151.5  5766.5   151.5  5836.5   152.2  5886.5   153.5  5968.5   153.7
#Mann= 6 ,-1 , 0
  4035.2      .2       0  4165.9     .12       0  4688.6     .05       0
  4966.4    .035       0  5035.6     .05       0  5836.5      .2       0
#XS Ineff= 2 , 0
       0    4660   152.8 5401.25       0  153.23
Permanent Ineff=
       F       F
Bank Sta=4966.4,5035.6
Exp/Cntr=0.5,0.3

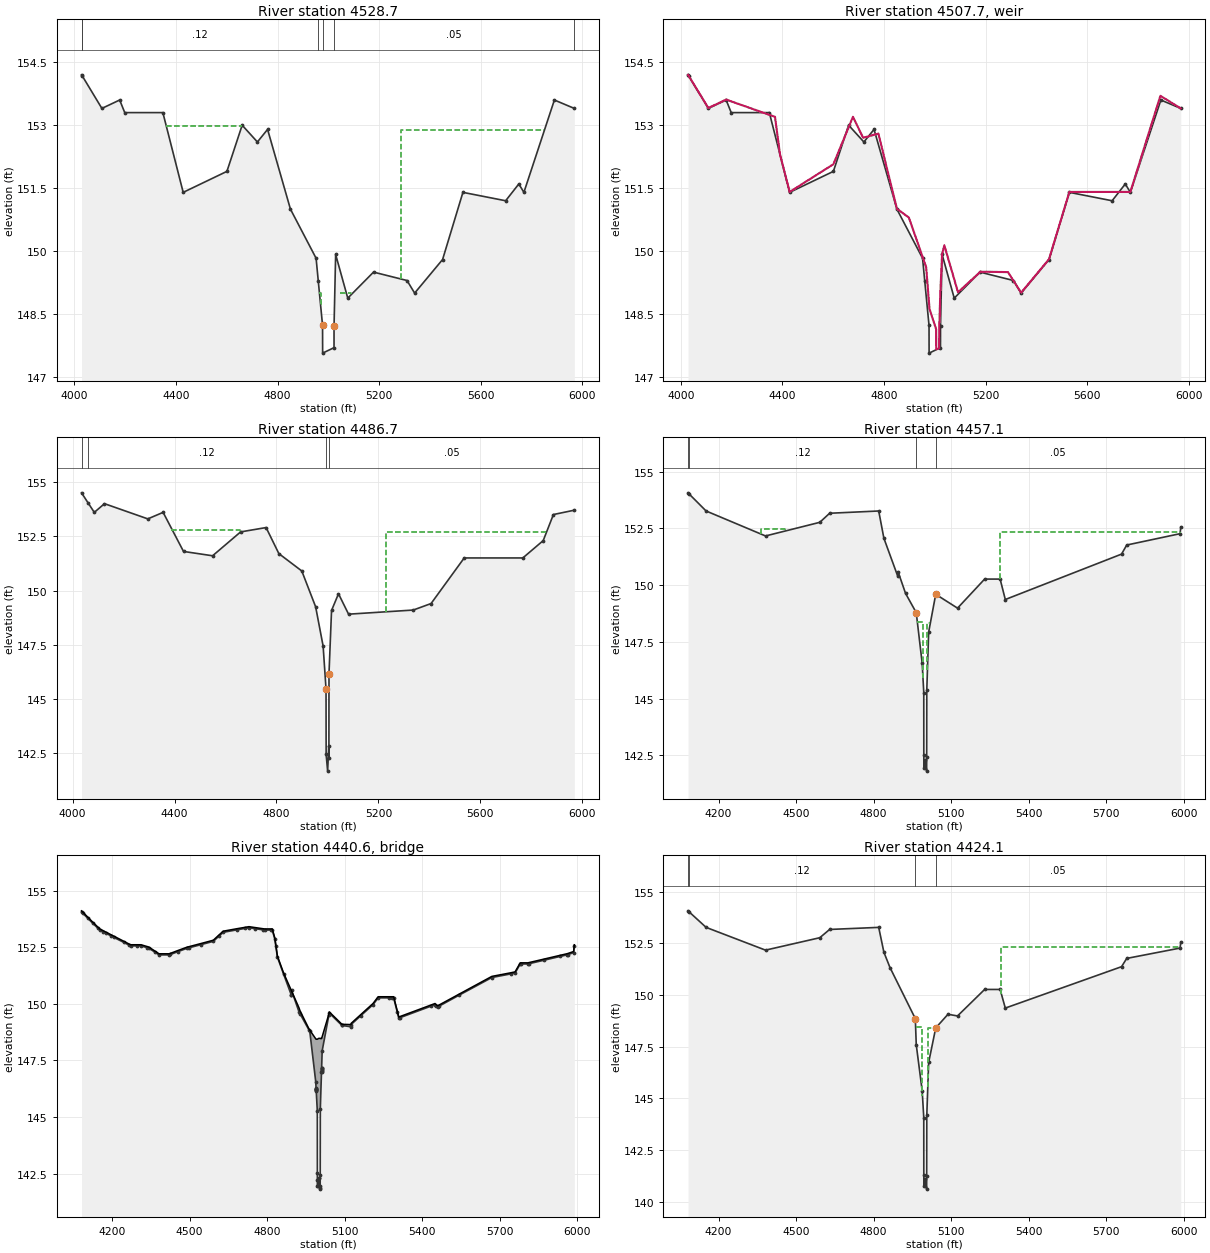
Type RM Length L Ch R = 1 ,4528.7  ,42,42,42
BEGIN DESCRIPTION:
Upstream Section of Inline Weir 1750-ft U.S. of Walden Way
END DESCRIPTION:
XS GIS Cut Line= 5
       3050408.6      13958194.7      3050195.02      13957729.3
      3050079.29      13957303.7      3050071.24      13957277.1
      3049782.08      13956366.3
#Sta/Elev= 30
  4028.8   154.2    4031  154.18  4108.8   153.4  4178.8   153.6  4198.8   153.3
  4348.8   153.3  4428.8   151.4  4600.9   151.9  4660.9     153  4720.9   152.6
  4760.9   152.9  4850.9     151  4951.9  149.83  4960.4  149.29  4977.3  148.23
  4977.6  147.57  5022.4   147.7  5022.5  148.21  5028.8  149.92  5076.5  148.88
  5177.9   149.5  5309.7   149.3  5339.7     149  5449.7   149.8  5529.7   151.4
  5697.9   151.2  5749.7   151.6  5769.7   151.4  5889.7   153.6  5968.1   153.4
#Mann= 6 ,-1 , 0
  4028.8      .2       0    4031     .12       0  4960.4     .05       0
  4977.3    .035       0  5022.5     .05       0  5968.1      .2       0
#XS Ineff= 4 ,-1
 4361.04 4659.52  152.99 4964.37 4969.37  149.01 5047.18 5091.12  149.01
 5284.22 5850.31  152.88
Permanent Ineff=
       F       F       F       F
Bank Sta=4977.3,5022.5
Exp/Cntr=0.5,0.3

Type RM Length L Ch R = 5 ,4507.7  ,,,
BEGIN DESCRIPTION:
Cross Section 4507.7
DAM 1750FT US WALDEN WAY
Structure ID: M116-00-00-04
END DESCRIPTION:
IW Pilot Flow=0
#Inline Weir SE= 30
  4028.8   154.2  4108.8  153.41  4178.8  153.61    4371   153.2    4391   152.3
  4428.8  151.41  4600.9  152.07  4677.9   153.2  4717.9   152.7  4777.9   152.8
  4850.9  151.01  4897.9   150.8  4965.9  149.62  4979.3  148.62  5005.2  148.14
  5005.5  147.66  5016.9  147.69  5017.6  148.16  5021.6  148.98  5028.8  149.93
  5037.5  150.14  5091.3  149.02  5179.7  149.51  5287.9   149.5  5339.7  149.01
  5449.7  149.81  5529.7  151.41  5769.7  151.41  5887.9   153.7  5968.1   153.4
IW Dist,WD,Coef,Skew,MaxSub,Min_El,Is_Ogee,SpillHt,DesHd
10,22,3,0,0.95,, 0 ,,,2,2,

Type RM Length L Ch R = 1 ,4486.7  ,29.6,29.6,29.6
BEGIN DESCRIPTION:
Downstream Section of Inline Weir 1750-ft U.S. of Walden Way
Cross Section FIELD_DS
Located At: DAM 1750FT US WALDEN WAY
END DESCRIPTION:
XS GIS Cut Line= 5
      3050458.38      13958177.9      3050256.58      13957734.8
      3050143.36      13957427.5      3050082.55      13957140.6
      3049823.26      13956350.8
#Sta/Elev= 30
  4035.2   154.5  4061.7  154.02  4085.2   153.6  4125.2     154  4295.2   153.3
  4355.2   153.6  4435.2   151.8  4549.3   151.6  4659.3   152.7  4759.3   152.9
  4809.3   151.7  4899.3   150.9  4953.6  149.25    4983  147.44  4994.4  145.46
  4994.8  142.45  5000.7  141.68  5005.1  142.84  5005.6   142.3    5006  146.16
    5016  149.08  5043.3  149.85  5082.8  148.91  5336.5   149.1  5406.5   149.4
  5536.5   151.5  5766.5   151.5  5846.5   152.3  5886.5   153.5  5968.5   153.7
#Mann= 4 ,-1 , 0
  4035.2      .2       0  4061.7     .12       0  4994.4     .06       0
    5006     .05       0
#XS Ineff= 2 ,-1
 4386.06 4657.73  152.78  5229.4 5859.09  152.69
Permanent Ineff=
       F       F
Bank Sta=4994.4,5006
Exp/Cntr=0.5,0.3

Type RM Length L Ch R = 1 ,4457.1  ,33,33,33
BEGIN DESCRIPTION:
Upstream Section of Shop Access Bridge 1700-feet U.S. of Walden Way Bridge
END DESCRIPTION:
XS GIS Cut Line= 3
      3050497.01      13958122.3      3050240.67      13957615.3
      3049832.42      13956334.9
#Sta/Elev= 30
  4081.7  154.07  4085.9  154.02  4151.7  153.27  4381.7  152.17  4591.7  152.77
  4629.9  153.17  4819.9  153.27  4839.9  152.07  4893.8  150.39  4894.6   150.6
  4923.8  149.64  4965.2  148.79  4988.2  146.56  4994.3  145.27  4994.5  142.51
  4994.7  141.95    5000   142.3  5005.4  141.81  5005.6  142.43    5006  145.37
  5013.2  147.93  5040.6   149.6    5125  148.99  5229.9  150.27  5289.9  150.27
  5309.9  149.37  5759.9  151.37  5779.9  151.77  5986.5  152.27  5989.2  152.57
#Mann= 4 ,-1 , 0
  4081.7      .2       0  4085.9     .12       0  4965.2     .06       0
  5040.6     .05       0
#XS Ineff= 4 ,-1
 4365.95  4455.9  152.46 4969.49 4991.98  148.37 5008.52 5019.83  148.34
 5290.03  5986.6  152.36
Permanent Ineff=
       F       F       F       F
Bank Sta=4965.2,5040.6
Exp/Cntr=0.5,0.3

Type RM Length L Ch R = 3 ,4440.6  ,,,
BEGIN DESCRIPTION:
SHOP ACCESS BRIDGE 1700FT US WALDEN WAY
Cross Section 4440.6
Structure ID: M116-00-00-03
END DESCRIPTION:
Bridge Culvert--1,0,-1,-1, 0
Deck Dist Width WeirC Skew NumUp NumDn MinLoCord MaxHiCord MaxSubmerge Is_Ogee
10,13,2.6,0, 91, 91, , , 0.95, 0, 1,1,,
  4081.7  4085.9  4105.9  4125.9  4145.9  4151.7  4165.9  4175.9  4245.9  4265.9
  4271.7  4295.9  4311.7  4335.9  4341.7  4365.9  4381.7  4421.7  4425.9  4455.9
  4491.7  4495.9  4545.9  4591.7  4613.5  4629.9  4683.5  4729.9  4753.5  4783.5
  4789.9  4813.5  4819.9  4829.9  4833.5  4839.9  4863.5  4923.8  4927.3  4961.6
  4965.2  4988.2 4989.51  4989.6 4990.01  4994.3    5000  5000.1  5004.8  5005.3
  5005.4  5005.6    5006 5010.49 5010.59  5010.7  5010.8 5010.91    5011    5039
  5040.6    5088  5089.5    5125  5125.1  5163.5  5209.9  5229.9  5273.5  5283.5
  5289.9  5303.5  5309.9  5313.5  5433.5  5449.9  5453.5  5459.9  5463.5  5669.9
  5743.5  5759.9  5779.9  5783.5  5809.9  5813.5  5873.5  5959.9  5963.5  5986.5
  5989.2
  154.12  154.07  153.84  153.61  153.39  153.32  153.24  153.18  152.77  152.65
  152.62  152.62  152.62  152.54  152.52  152.34  152.22  152.22  152.24  152.37
  152.52  152.53  152.68  152.82  153.05  153.22  153.33  153.42  153.38  153.33
  153.32  153.32  153.32  152.92  152.63  152.12  151.38  149.82   149.7  148.91
  148.84  148.46  148.44  148.44  148.44  148.44  148.48  148.48  148.48  148.48
  148.47  148.47  148.47  148.47  148.47  148.47  148.47  148.47  148.47  149.55
  149.65  149.12   149.1  149.09  149.14  149.54  150.02  150.32  150.32  150.32
  150.32  149.71  149.42  149.44  149.95  150.02  149.98  149.92  149.94  151.22
  151.38  151.42  151.82  151.82  151.82  151.83  151.99  152.22  152.23  152.32
  152.62
                                                                                
                                                                                
                                                                                
                                                                                
  145.64  145.26  145.24  145.24  145.24  145.24  145.28  145.28  145.28  145.28
  145.27  145.27  145.27  145.27  145.27  145.27  145.27  145.27  145.27
                                                                                
                                                                                
                                                                                
        
  4081.7  4085.9  4105.9  4125.9  4145.9  4151.7  4165.9  4175.9  4245.9  4265.9
  4271.7  4295.9  4311.7  4335.9  4341.7  4365.9  4381.7  4421.7  4425.9  4455.9
  4491.7  4495.9  4545.9  4591.7  4613.5  4629.9  4683.5  4729.9  4753.5  4783.5
  4789.9  4813.5  4819.9  4829.9  4833.5  4839.9  4863.5  4923.8  4927.3  4961.6
  4965.2  4988.2 4989.51  4989.6 4990.01  4994.3    5000  5000.1  5004.8  5005.3
  5005.4  5005.6    5006 5010.49 5010.59  5010.7  5010.8 5010.91    5011    5039
  5040.6    5088  5089.5    5125  5125.1  5163.5  5209.9  5229.9  5273.5  5283.5
  5289.9  5303.5  5309.9  5313.5  5433.5  5449.9  5453.5  5459.9  5463.5  5669.9
  5743.5  5759.9  5779.9  5783.5  5809.9  5813.5  5873.5  5959.9  5963.5  5986.5
  5989.2
   153.5  153.46  153.23     153  152.78  152.71  152.63  152.57  152.16  152.04
  152.01  152.01  152.01  151.93  151.91  151.73  151.61  151.61  151.63  151.76
  151.91  151.92   152.5  152.57   152.6  152.62  152.72   152.8  152.77   152.8
  152.71  152.71  152.71  152.31   152.3  152.04   151.1  149.82   149.7  148.76
  148.72  148.46  148.44  148.44  148.44  148.44  148.48  148.48  148.48  148.48
  148.47  148.47  148.47  148.47  148.47  148.47  148.47  148.47  148.47  149.18
  149.17  148.98  148.98  149.09  149.09   149.2  149.45  149.71   149.8  149.71
  149.71   149.1  148.81  148.83   149.4  149.41  149.37  149.31  149.33  150.61
  150.77  150.81  151.21  151.21  151.21  151.22   151.5  151.74   151.7  151.97
     152
                                                                                
                                                                                
                                                                                
                                                                                
  145.64  145.26  145.24  145.24  145.24  145.24  145.28  145.28  145.28  145.28
  145.27  145.27  145.27  145.27  145.27  145.27  145.27  145.27  145.27
                                                                                
                                                                                
                                                                                
        
Abutment Skew #Up #Dn= , 2 , 2
  4989.6  4994.6
  146.27  142.28
  4989.6  4994.6
  145.02  141.03
Abutment Skew #Up #Dn= , 2 , 2
  5005.3 5010.69
  141.89  147.02
  5005.3 5010.69
  140.64  145.77
BR Coef= 1 , 1 , 0 ,1.25, 0 ,,,0.8,0,2,0,
WSPro=,,,, 1 ,,,, 0 ,,,, 0 ,,,,-1 ,-1 ,-1 , 0 , 0 , 0 , 0 , 0
BR U #Sta/Elev= 109
  4081.7  154.07  4085.9  154.02  4105.9  153.79  4125.9  153.56  4145.9  153.34
  4151.7  153.27  4165.9  153.19  4175.9  153.13  4195.9  153.01  4205.9  152.95
  4245.9  152.72  4265.9   152.6  4271.7  152.57  4295.9  152.57  4311.7  152.57
  4335.9  152.49  4341.7  152.47  4365.9  152.29  4381.7  152.17  4421.7  152.17
  4425.9  152.19  4455.9  152.32  4491.7  152.47  4495.9  152.48  4545.9  152.63
  4591.7  152.77  4613.5     153  4629.9  153.17  4683.5  153.28  4713.5  153.34
  4729.9  153.37  4753.5  153.33  4783.5  153.28  4789.9  153.27  4813.5  153.27
  4819.9  153.27  4829.9  152.87  4833.5  152.58  4839.9  152.07  4863.5  151.33
  4893.5   150.4  4893.8  150.39  4894.6   150.6  4923.8  149.64  4927.3  149.57
  4961.6  148.86  4965.2  148.79  4988.2  146.56 4989.51  146.28  4989.6  146.26
 4989.69  146.24  4989.8  146.22  4989.9   146.2 4990.01  146.18  4990.2  146.14
  4994.3  145.27  4994.5  142.51  4994.6  142.23  4994.7  141.95  4995.4  141.94
    5000   142.3  5000.1  142.29  5004.8  141.97  5005.3  141.84  5005.4  141.81
  5005.6  142.43    5006  145.37 5010.49  146.97 5010.59     147  5010.7  147.04
  5010.8  147.08 5010.91  147.12    5011  147.15  5011.1  147.18  5013.2  147.93
    5039   149.5  5040.6   149.6    5088  149.07  5089.5  149.05    5125  148.99
  5125.1  149.09  5163.5  149.49  5209.9  149.97  5229.9  150.27  5273.5  150.27
  5283.5  150.27  5289.9  150.27  5303.5  149.66  5309.9  149.37  5313.5  149.39
  5433.5   149.9  5449.9  149.97  5453.5  149.93  5459.9  149.87  5463.5  149.89
  5543.5  150.39  5669.9  151.17  5743.5  151.33  5759.9  151.37  5779.9  151.77
  5783.5  151.77  5809.9  151.77  5813.5  151.78  5873.5  151.94  5933.5   152.1
  5959.9  152.17  5963.5  152.18  5986.5  152.27  5989.2  152.57
BR U #Mann= 4
  4081.7      .2  4085.9     .12  4965.2     .05  5040.6     .05
BR D #Sta/Elev= 109
  4081.7  154.07  4085.9  154.02  4105.9  153.79  4125.9  153.56  4145.9  153.34
  4151.7  153.27  4165.9  153.19  4175.9  153.13  4195.9  153.01  4205.9  152.95
  4245.9  152.72  4265.9   152.6  4271.7  152.57  4295.9  152.57  4311.7  152.57
  4335.9  152.49  4341.7  152.47  4365.9  152.29  4381.7  152.17  4421.7  152.17
  4425.9  152.19  4455.9  152.32  4491.7  152.47  4495.9  152.48  4545.9  152.63
  4591.7  152.77  4613.5     153  4629.9  153.17  4683.5  153.28  4713.5  153.34
  4729.9  153.37  4753.5  153.33  4783.5  153.28  4789.9  153.27  4813.5  153.27
  4819.9  153.27  4829.9  152.87  4833.5  152.58  4839.9  152.07  4863.5  151.33
  4893.5   150.4  4893.8  150.39  4894.6   150.6  4923.8  149.64  4927.3  149.57
  4961.6  148.86  4965.2   147.6  4988.2  145.37 4989.51  145.09  4989.6  145.07
 4989.69  145.05  4989.8  145.03  4989.9  145.01 4990.01  144.99  4990.2  144.95
  4994.3  144.08  4994.5  141.32  4994.6  141.04  4994.7  140.76  4995.4  140.75
    5000  141.11  5000.1   141.1  5004.8  140.78  5005.3  140.65  5005.4  140.62
  5005.6  141.24    5006  144.18 5010.49  145.78 5010.59  145.81  5010.7  145.85
  5010.8  145.89 5010.91  145.93    5011  145.96  5011.1  145.99  5013.2  146.74
    5039  148.31  5040.6  148.41    5088  149.07  5089.5  149.05    5125  148.99
  5125.1  149.09  5163.5  149.49  5209.9  149.97  5229.9  150.27  5273.5  150.27
  5283.5  150.27  5289.9  150.27  5303.5  149.66  5309.9  149.37  5313.5  149.39
  5433.5   149.9  5449.9  149.97  5453.5  149.93  5459.9  149.87  5463.5  149.89
  5543.5  150.39  5669.9  151.17  5743.5  151.33  5759.9  151.37  5779.9  151.77
  5783.5  151.77  5809.9  151.77  5813.5  151.78  5873.5  151.94  5933.5   152.1
  5959.9  152.17  5963.5  152.18  5986.5  152.27  5989.2  152.57
BR D #Mann= 4
  4081.7      .2  4085.9     .12  4961.6     .05  5040.6     .05
BC Design=,, 0 ,, 0 ,,,,,,
BC HTab HWMax=154.07

Type RM Length L Ch R = 1 ,4424.1  ,146.3,146.3,146.3
BEGIN DESCRIPTION:
Downstream Section of Shop Access Bridge 1700-feet U.S. of Walden Way Bridge
END DESCRIPTION:
XS GIS Cut Line= 4
       3050555.4      13958064.5      3050223.04      13957405.2
      3050104.02      13957094.5      3049876.77      13956298.3
#Sta/Elev= 30
  4081.7  154.07  4085.9  154.02  4151.7  153.27  4381.7  152.17  4591.7  152.77
  4629.9  153.17  4819.9  153.27  4839.9  152.07  4863.5  151.33  4961.6  148.86
  4965.2   147.6  4988.2  145.37  4994.3  144.08  4994.5  141.32  4994.7  140.76
    5000  141.11  5005.4  140.62  5005.6  141.24    5006  144.18  5013.2  146.74
  5040.6  148.41    5088  149.07    5125  148.99  5229.9  150.27  5289.9  150.27
  5309.9  149.37  5759.9  151.37  5779.9  151.77  5986.5  152.27  5989.2  152.57
#Mann= 4 ,-1 , 0
  4081.7      .2       0  4085.9     .12       0  4961.6     .06       0
  5040.6     .05       0
#XS Ineff= 3 ,-1
 4962.73 4989.27  148.46 5009.92  5042.1  148.42 5295.14 5986.54   152.3
Permanent Ineff=
       F       F       F
Bank Sta=4961.6,5040.6
Exp/Cntr=0.5,0.3