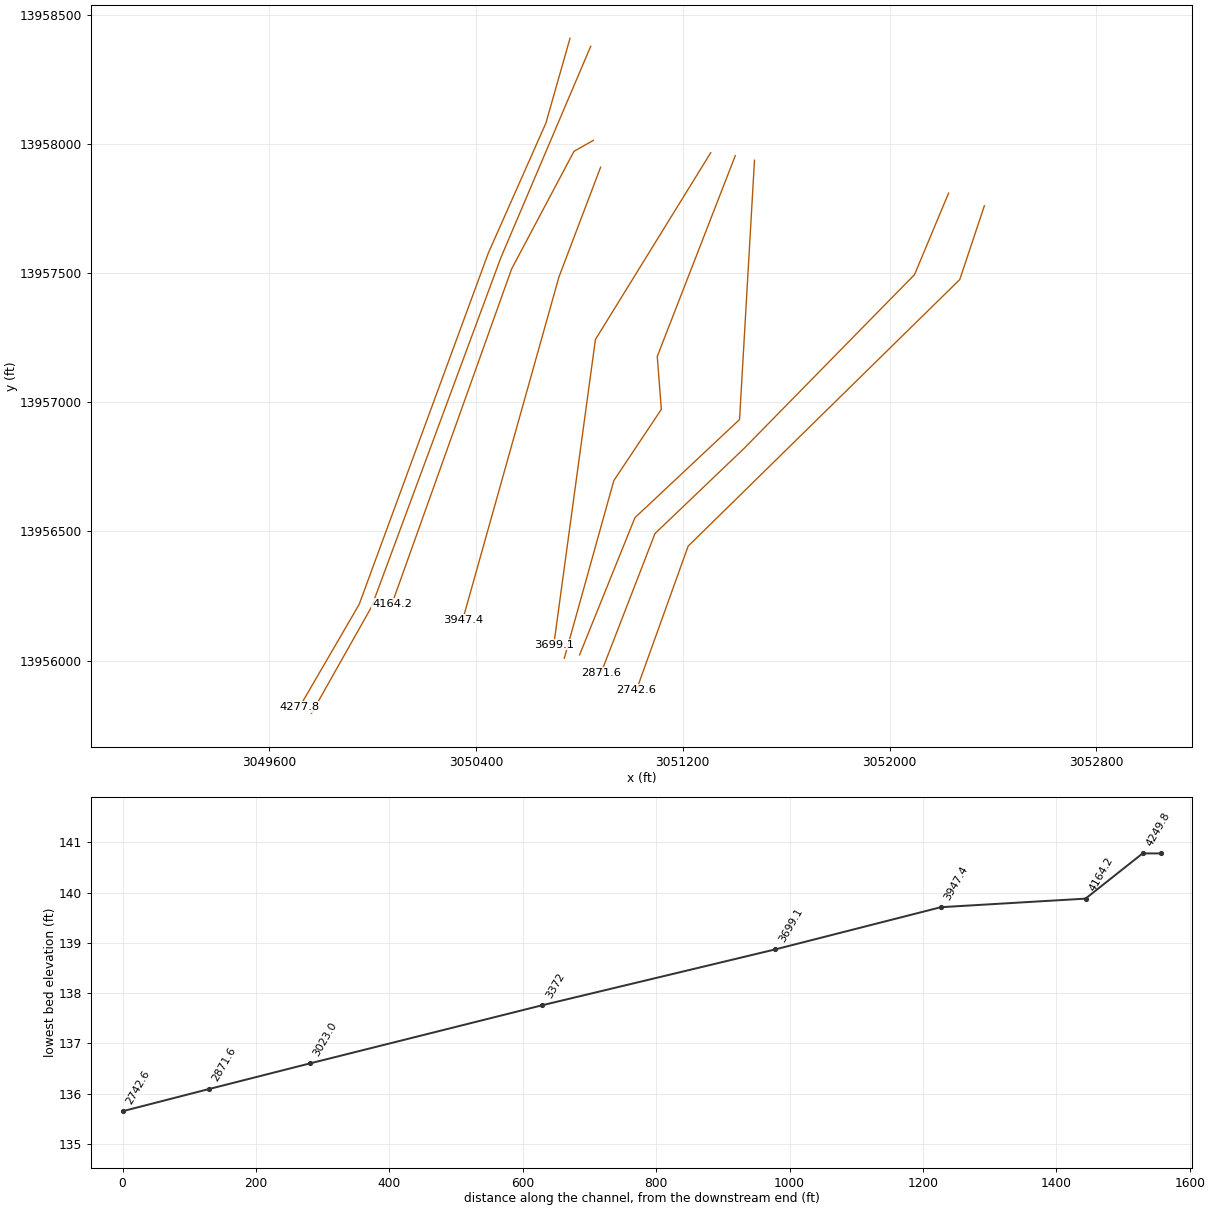
HEC-RAS study M116-00-00.PRJ: M116-00-00

--- M116-00-00.g01 (geometry) --- (continued)

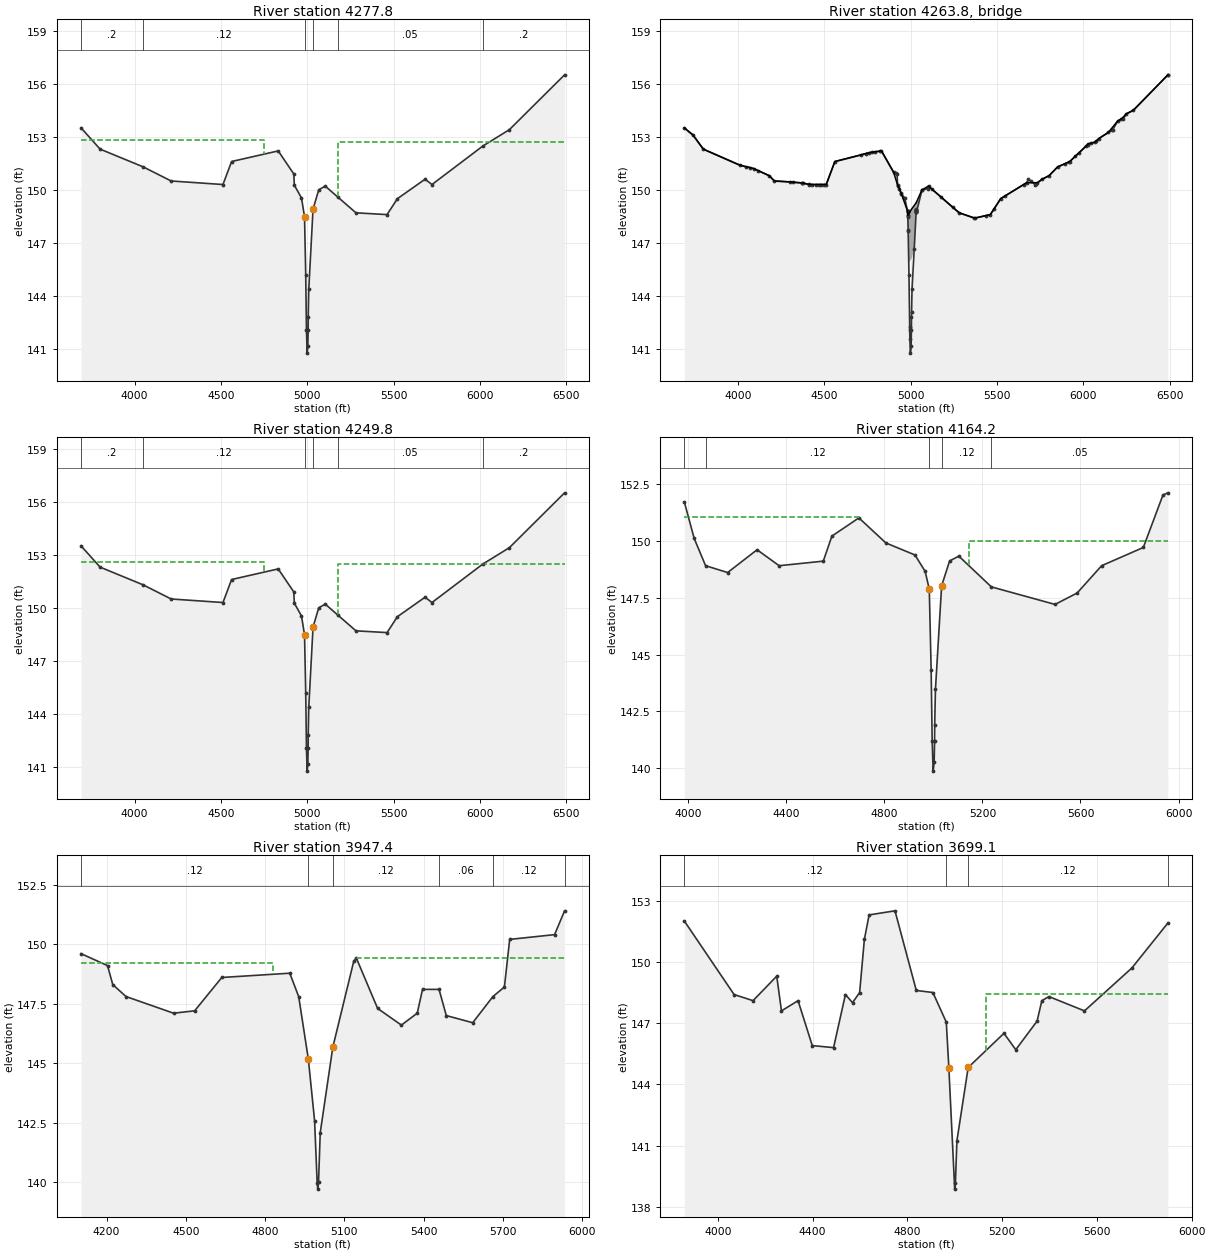
Type RM Length L Ch R = 1 ,4277.8  ,28,28,28
BEGIN DESCRIPTION:
Upstream Section of Lenze Road Bridge
END DESCRIPTION:
XS GIS Cut Line= 5
      3050763.76      13958408.1      3050670.43      13958079.9
      3050447.81      13957577.2      3049948.29       13956218.
      3049717.47      13955820.7
#Sta/Elev= 30
  3690.6  153.51  3800.6  152.31  4049.4  151.31  4211.8  150.51  4511.8  150.31
  4561.8  151.61  4831.6  152.21  4921.6  150.91    4925  150.27  4966.3  149.55
 4983.91  148.49  4990.8  145.22    4995  142.09    4999  140.78  5003.1  141.16
  5004.9  142.11  5005.3  142.82  5008.4  144.38  5033.1  148.92  5066.2  150.01
  5103.8  150.22  5176.6   149.6  5281.6  148.71  5461.6  148.61  5521.6  149.51
  5681.6  150.61  5721.6  150.31  6015.3  152.48  6169.6  153.41  6489.1  156.51
#Mann= 6 ,-1 , 0
  3690.6      .2       0  4049.4     .12       0 4983.91     .06       0
  5033.1     .12       0  5176.6     .05       0  6015.3      .2       0
#XS Ineff= 2 , 0
         4748.25  152.85 5178.28          152.73
Permanent Ineff=
       F       F
Bank Sta=4983.91,5033.1
Exp/Cntr=0.5,0.3

Type RM Length L Ch R = 3 ,4263.8  ,,,
BEGIN DESCRIPTION:
SHOP ACCESS BRIDGE 1500FT US WALDEN WAY
Cross Section 4263.8
Structure ID: M116-00-00-02
END DESCRIPTION:
Bridge Culvert--1,0,-1,-1, 0
Deck Dist Width WeirC Skew NumUp NumDn MinLoCord MaxHiCord MaxSubmerge Is_Ogee
10,8,2.6,0, 105, 105, , , 0.95, 0, 1,1,,
  3690.6  3740.6  3800.6  4010.6  4049.4  4069.4  4091.8  4119.4  4181.8  4211.8
  4299.4  4319.4  4379.4  4409.4  4411.8  4429.4  4451.8  4469.4  4479.4  4499.4
  4511.8  4561.8  4714.6  4744.6  4761.6  4774.6  4794.6  4824.6  4831.6  4901.6
    4925  4929.1  4934.6  4945.6  4947.2  4982.3 4982.41  4982.5  4982.6  4983.2
 4983.69  4983.8 4983.91  4985.9    4986  4990.8  4994.8    4995  4996.1    4999
  5003.1  5004.9  5005.3  5005.9  5008.4    5021  5033.1  5033.2 5033.29  5033.4
 5033.49  5033.6  5033.7 5033.81    5034  5034.1  5066.2    5068  5103.8  5124.6
  5176.6  5244.6  5281.6  5364.6  5371.6  5434.6  5461.6  5484.6  5521.6  5544.6
  5654.6  5671.6  5734.6  5761.6  5801.6  5851.6  5894.6  5914.6  5921.6  5954.6
  5974.6  6015.3  6025.3  6029.6  6045.3  6069.6  6075.3  6089.6  6145.3  6199.6
  6219.6  6249.6  6289.6  6488.3  6489.1
  153.52  153.12  152.32  151.42  151.32  151.28  151.22   151.1  150.82  150.52
  150.47  150.45   150.4  150.33  150.32  150.32  150.32  150.32  150.32  150.32
  150.32  151.62     152  152.08  152.12  152.14  152.17  152.21  152.22  151.02
  150.28  150.22  150.09  149.82  149.78  148.82  148.82  148.81  148.81  148.78
  148.59  148.57  148.57   148.6   148.6  148.68  148.75  148.75  148.77  148.82
  148.88  148.91  148.92  148.93  148.96  149.13  149.29  149.29  149.29  149.29
   149.3   149.3   149.3   149.3  149.32  149.32  150.02  150.02  150.23  150.05
  149.61  149.03  148.72  148.44  148.42  148.56  148.62  148.96  149.52  149.66
  150.32  150.42  150.42  150.62  150.82  151.32   151.5  151.59  151.62  151.93
  152.11  152.49  152.58  152.62  152.66  152.72  152.78  152.92  153.27  153.92
  154.02  154.32  154.52  156.51  156.52
                                                                                
                                                                                
                                                                                
                                                                                
                  145.77   145.8   145.8  145.88  145.95  145.95  145.97  146.02
  146.08  146.11  146.12  146.13  146.16  146.33
                                                                                
                                                                                
                                                                                
                                                                                
                                        
  3690.6  3740.6  3800.6  4010.6  4049.4  4069.4  4091.8  4119.4  4181.8  4211.8
  4299.4  4319.4  4379.4  4409.4  4411.8  4429.4  4451.8  4469.4  4479.4  4499.4
  4511.8  4561.8  4714.6  4744.6  4761.6  4774.6  4794.6  4824.6  4831.6  4901.6
    4925  4929.1  4934.6  4945.6  4947.2  4982.3 4982.41  4982.5  4982.6  4983.2
 4983.69  4983.8 4983.91  4985.9    4986  4990.8  4994.8    4995  4996.1    4999
  5003.1  5004.9  5005.3  5005.9  5008.4    5021  5033.1  5033.2 5033.29  5033.4
 5033.49  5033.6  5033.7 5033.81    5034  5034.1  5066.2    5068  5103.8  5124.6
  5176.6  5244.6  5281.6  5364.6  5371.6  5434.6  5461.6  5484.6  5521.6  5544.6
  5654.6  5671.6  5734.6  5761.6  5801.6  5851.6  5894.6  5914.6  5921.6  5954.6
  5974.6  6015.3  6025.3  6029.6  6045.3  6069.6  6075.3  6089.6  6145.3  6199.6
  6219.6  6249.6  6289.6  6488.3  6489.1
  153.52  153.12  152.32  151.42  151.32  151.28  151.22   151.1  150.82  150.52
  150.47  150.45   150.4  150.33  150.32  150.32  150.32  150.32  150.32  150.32
  150.32  151.62     152  152.08  152.12  152.14  152.17  152.21  152.22  151.02
  150.28  150.22  150.09  149.82  149.78  148.82  148.82  148.81  148.81  148.78
  148.59  148.57  148.57   148.6   148.6  148.68  148.75  148.75  148.77  148.82
  148.88  148.91  148.92  148.93  148.96  149.13  149.29  149.29  149.29  149.29
   149.3   149.3   149.3   149.3  149.32  149.32  150.02  150.02  150.23  150.05
  149.61  149.03  148.72  148.44  148.42  148.56  148.62  148.96  149.52  149.66
  150.32  150.42  150.42  150.62  150.82  151.32   151.5  151.59  151.62  151.93
  152.11  152.49  152.58  152.62  152.66  152.72  152.78  152.92  153.27  153.92
  154.02  154.32  154.52  156.51  156.52
                                                                                
                                                                                
                                                                                
                                                                                
                  145.77   145.8   145.8  145.88  145.95  145.95  145.97  146.02
  146.08  146.11  146.12  146.13  146.16  146.33
                                                                                
                                                                                
                                                                                
                                                                                
                                        
Abutment Skew #Up #Dn= , 2 , 2
  4982.3    4986
  148.81  147.69
  4982.3    4986
  147.98  146.86
BR Coef= 1 , 1 , 0 ,1.25, 0 ,,,0.8,0,2,0,
WSPro=,,,, 1 ,,,, 0 ,,,, 0 ,,,,-1 ,-1 ,-1 , 0 , 0 , 0 , 0 , 0
BR U #Sta/Elev= 119
  3690.6  153.51  3740.6  153.11  3800.6  152.31  4010.6  151.41  4049.4  151.31
  4069.4  151.27  4091.8  151.21  4119.4  151.09  4181.8  150.81  4211.8  150.51
  4299.4  150.46  4319.4  150.44  4369.4  150.41  4371.8  150.41  4379.4  150.39
  4409.4  150.32  4411.8  150.31  4429.4  150.31  4451.8  150.31  4469.4  150.31
  4479.4  150.31  4499.4  150.31  4511.8  150.31  4561.8  151.61  4714.6  151.99
  4744.6  152.07  4761.6  152.11  4774.6  152.13  4794.6  152.16  4824.6   152.2
  4831.6  152.21  4901.6  151.01  4914.6  150.95  4921.6  150.91    4925  150.27
  4929.1  150.21  4934.6  150.08  4945.6  149.81  4947.2  149.77  4964.5  149.57
  4966.3  149.55  4982.3  148.81 4982.41  148.81  4982.5   148.8  4982.6   148.8
  4983.2  148.77 4983.69  148.58  4983.8  148.54 4983.91  148.49  4985.9  147.72
    4986  147.68  4990.8  145.22  4994.8  142.28    4995  142.09  4996.1  141.57
    4999  140.78  5003.1  141.16  5004.9  142.11  5005.3  142.82  5005.9  143.12
  5008.4  144.38    5021  146.65  5033.1  148.92  5033.2   148.9 5033.29  148.89
  5033.4  148.87 5033.49  148.85  5033.6  148.83  5033.7  148.81 5033.81  148.79
    5034  148.76  5034.1  148.74  5066.2  150.01    5068  150.01  5101.7  150.09
  5103.8  150.22  5124.6  150.04  5176.6   149.6  5244.6  149.02  5281.6  148.71
  5364.6  148.43  5371.6  148.41  5434.6  148.55  5461.6  148.61  5484.6  148.95
  5521.6  149.51  5544.6  149.65  5654.6  150.31  5671.6  150.41  5681.6  150.61
  5694.6  150.51  5721.6  150.31  5724.6  150.33  5734.6  150.41  5761.6  150.61
  5801.6  150.81  5851.6  151.31  5894.6  151.49  5914.6  151.58  5921.6  151.61
  5954.6  151.92  5974.6   152.1  6015.3  152.48  6025.3  152.57  6029.6  152.61
  6045.3  152.65  6069.6  152.71  6075.3  152.77  6089.6  152.91  6145.3  153.26
  6165.3  153.38  6169.6  153.41  6199.6  153.91  6219.6  154.01  6229.6  154.01
  6249.6  154.31  6289.6  154.51  6488.3   156.5  6489.1  156.51
BR U #Mann= 6
  3690.6      .2  4049.4     .12 4983.91     .05  5033.1     .12  5176.6     .05
  6015.3      .2
BR D #Sta/Elev= 119
  3690.6  153.51  3740.6  153.11  3800.6  152.31  4010.6  151.41  4049.4  151.31
  4069.4  151.27  4091.8  151.21  4119.4  151.09  4181.8  150.81  4211.8  150.51
  4299.4  150.46  4319.4  150.44  4369.4  150.41  4371.8  150.41  4379.4  150.39
  4409.4  150.32  4411.8  150.31  4429.4  150.31  4451.8  150.31  4469.4  150.31
  4479.4  150.31  4499.4  150.31  4511.8  150.31  4561.8  151.61  4714.6  151.99
  4744.6  152.07  4761.6  152.11  4774.6  152.13  4794.6  152.16  4824.6   152.2
  4831.6  152.21  4901.6  151.01  4914.6  150.95  4921.6  150.91    4925  150.27
  4929.1  150.21  4934.6  150.08  4945.6  149.81  4947.2  149.77  4964.5  149.57
  4966.3  149.55  4982.3  148.81 4982.41  148.81  4982.5   148.8  4982.6   148.8
  4983.2  148.77 4983.69  148.58  4983.8  148.54 4983.91  148.49  4985.9  147.72
    4986  147.68  4990.8  145.22  4994.8  142.28    4995  142.09  4996.1  141.57
    4999  140.78  5003.1  141.16  5004.9  142.11  5005.3  142.82  5005.9  143.12
  5008.4  144.38    5021  146.65  5033.1  148.92  5033.2   148.9 5033.29  148.89
  5033.4  148.87 5033.49  148.85  5033.6  148.83  5033.7  148.81 5033.81  148.79
    5034  148.76  5034.1  148.74  5066.2  150.01    5068  150.01  5101.7  150.09
  5103.8  150.22  5124.6  150.04  5176.6   149.6  5244.6  149.02  5281.6  148.71
  5364.6  148.43  5371.6  148.41  5434.6  148.55  5461.6  148.61  5484.6  148.95
  5521.6  149.51  5544.6  149.65  5654.6  150.31  5671.6  150.41  5681.6  150.61
  5694.6  150.51  5721.6  150.31  5724.6  150.33  5734.6  150.41  5761.6  150.61
  5801.6  150.81  5851.6  151.31  5894.6  151.49  5914.6  151.58  5921.6  151.61
  5954.6  151.92  5974.6   152.1  6015.3  152.48  6025.3  152.57  6029.6  152.61
  6045.3  152.65  6069.6  152.71  6075.3  152.77  6089.6  152.91  6145.3  153.26
  6165.3  153.38  6169.6  153.41  6199.6  153.91  6219.6  154.01  6229.6  154.01
  6249.6  154.31  6289.6  154.51  6488.3   156.5  6489.1  156.51
BR D #Mann= 6
  3690.6      .2  4049.4     .12 4983.91     .05  5033.1     .12  5176.6     .05
  6015.3      .2
BR D Banks=,5033.1
BC Design=,, 0 ,, 0 ,,,,,,
BC HTab HWMax=156.51

Type RM Length L Ch R = 1 ,4249.8  ,85.6,85.6,85.6
BEGIN DESCRIPTION:
Downstream Section of Lenze Road Bridge
END DESCRIPTION:
XS GIS Cut Line= 4
    3050843.7825   13958377.2702      3050496.25      13957559.3
      3049996.06      13956208.2      3049763.93      13955796.2
#Sta/Elev= 30
  3690.6  153.51  3800.6  152.31  4049.4  151.31  4211.8  150.51  4511.8  150.31
  4561.8  151.61  4831.6  152.21  4921.6  150.91    4925  150.27  4966.3  149.55
 4983.91  148.49  4990.8  145.22    4995  142.09    4999  140.78  5003.1  141.16
  5004.9  142.11  5005.3  142.82  5008.4  144.38  5033.1  148.92  5066.2  150.01
  5103.8  150.22  5176.6   149.6  5281.6  148.71  5461.6  148.61  5521.6  149.51
  5681.6  150.61  5721.6  150.31  6015.3  152.48  6169.6  153.41  6489.1  156.51
#Mann= 6 ,-1 , 0
  3690.6      .2       0  4049.4     .12       0 4983.91     .06       0
  5033.1     .12       0  5176.6     .05       0  6015.3      .2       0
#XS Ineff= 2 , 0
         4749.49  152.61 5179.08           152.5
Permanent Ineff=
       F       F
Bank Sta=4983.91,5033.1
Exp/Cntr=0.5,0.3

Type RM Length L Ch R = 1 ,4164.2  ,202.76,216.8,229.02
BEGIN DESCRIPTION:
Cross Section 4164.2
Cross Section XS-06
END DESCRIPTION:
XS GIS Cut Line= 4
     3050854.344   13958013.4186      3050779.23       13957971.
      3050537.93      13957515.9      3050074.99      13956219.6
#Sta/Elev= 30
  3984.4   151.7  4024.4   150.1    4071   148.9    4161   148.6    4281   149.6
    4371   148.9    4551   149.1  4586.2   150.2  4696.2     151  4806.2   149.9
  4925.1  149.37  4966.4  148.65  4983.3  147.87  4990.9  144.32  4995.1  141.19
  4999.1  139.88  5003.2  140.26    5005  141.21  5005.4  141.92  5008.5  143.48
  5033.7  148.02  5066.3  149.11  5103.9  149.32  5236.5  147.97  5496.2   147.2
  5586.2   147.7  5686.2   148.9  5856.2   149.7  5936.2     152  5956.2   152.1
#Mann= 5 ,-1 , 0
  3984.4      .2       0    4071     .12       0  4983.3     .06       0
  5033.7     .12       0  5236.5     .05       0
#XS Ineff= 2 , 0
       0 4696.22  151.02 5144.18       0  149.97
Permanent Ineff=
       F       F
Bank Sta=4983.3,5033.7
Exp/Cntr=0.3,0.1

Type RM Length L Ch R = 1 ,3947.4  ,210.3,248.3,259.71
BEGIN DESCRIPTION:
Cross Section 3947.4
Cross Section XS-05
END DESCRIPTION:
XS GIS Cut Line= 3
    3050882.0629   13957909.2123        3050721.      13957484.9
      3050348.78      13956158.4
#Sta/Elev= 30
  4103.6   149.6  4203.6   149.1  4223.6   148.3  4273.6   147.8  4453.6   147.1
  4533.6   147.2  4636.3   148.6  4893.7  148.78  4927.6  147.79  4964.1  145.16
  4987.6  142.59  4997.4  139.98  4999.6  139.71  5002.6  140.01    5009  142.08
  5056.6  145.67  5136.3   149.3  5146.3   149.4  5226.3   147.3  5316.3   146.6
  5376.3   147.1  5396.3   148.1  5458.8   148.1  5486.3     147  5586.3   146.7
  5662.9   147.8  5706.3   148.2  5726.3   150.2  5896.3   150.4  5934.1   151.4
#Mann= 6 ,-1 , 0
  4103.6     .12       0  4964.1     .06       0  5056.6     .12       0
  5458.8     .06       0  5662.9     .12       0  5934.1      .2       0
#XS Ineff= 2 , 0
       0 4830.36  149.19 5146.81       0  149.41
Permanent Ineff=
       F       F
Bank Sta=4964.1,5056.6
Exp/Cntr=0.3,0.1

Type RM Length L Ch R = 1 ,3699.1  ,250.6,349,217
BEGIN DESCRIPTION:
Cross Section xs4.75
END DESCRIPTION:
XS GIS Cut Line= 3
      3051308.05      13957965.5      3050862.09      13957242.9
      3050701.05      13956061.9
#Sta/Elev= 30
  3858.3     152  4068.3   148.4  4148.3   148.1  4248.3   149.3  4268.3   147.6
  4338.3   148.1  4398.3   145.9  4488.3   145.8  4538.3   148.4  4568.3     148
  4598.3   148.5  4618.3   151.1  4638.3   152.3  4747.5   152.5  4837.5   148.6
  4907.5   148.5  4964.1  147.05 4974.89  144.82  4999.6  138.87  5002.6  139.17
    5009  141.24  5056.6  144.83  5207.5   146.5  5257.5   145.7  5347.5   147.1
  5367.5   148.1  5397.5   148.3  5547.5   147.6  5747.5   149.7  5899.4   151.9
#Mann= 4 ,-1 , 0
  3858.3     .12       0  4964.1     .06       0  5056.6     .12       0
  5899.4      .2       0
#XS Ineff= 2 , 0
       0 4601.43  148.65 5130.71       0  148.44
Permanent Ineff=
       F       F
Bank Sta=4974.89,5056.6
Exp/Cntr=0.3,0.1

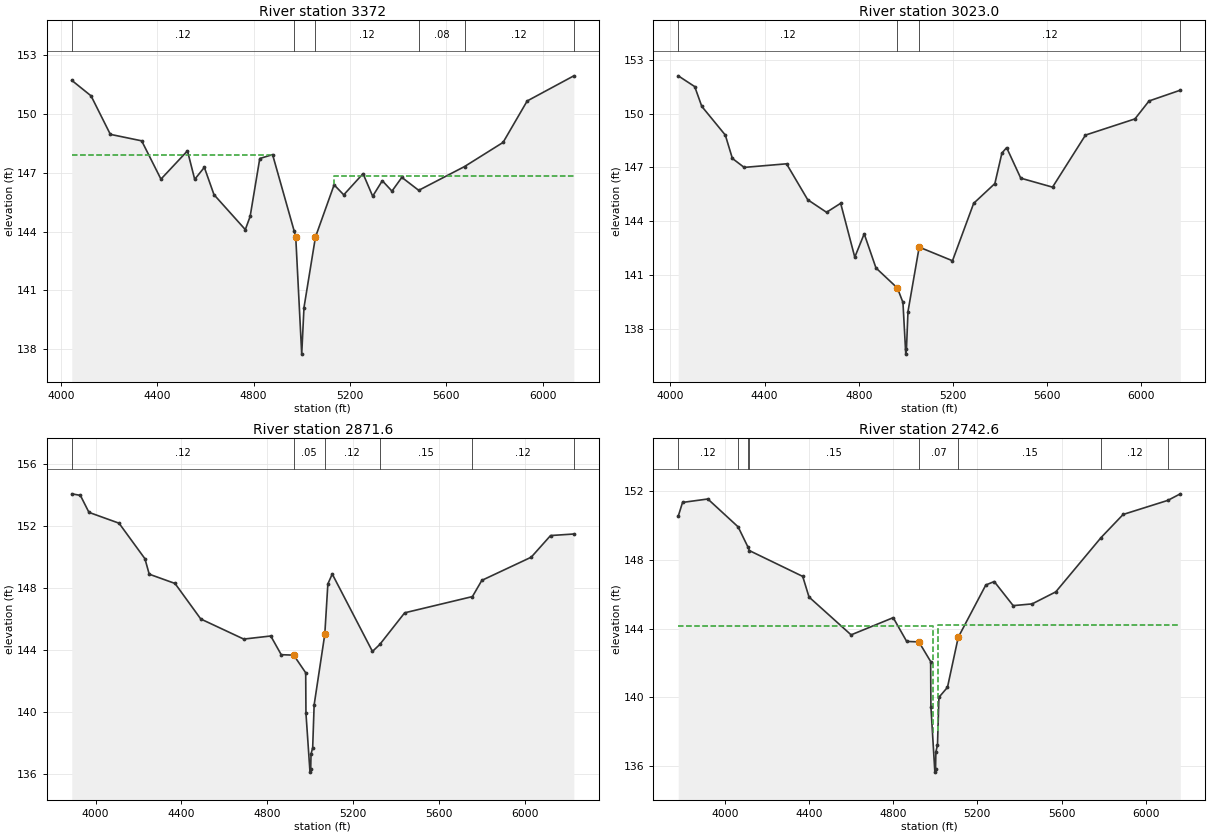
Type RM Length L Ch R = 1 ,3372    ,349,349,349
BEGIN DESCRIPTION:
Cross Section XS 4.35
END DESCRIPTION:
XS GIS Cut Line= 5
      3051402.96      13957953.8      3051101.26     13957177.27
        3051117.     13956972.63      3050933.35     13956697.16
      3050741.83     13956009.79
#Sta/Elev= 30
  4045.6   151.7  4125.6  150.91  4205.6  148.95  4335.6  148.62  4415.6  146.67
  4525.6  148.11  4555.6  146.66  4595.6  147.27  4635.6  145.88  4765.6   144.1
  4785.6  144.77  4825.6  147.72  4878.7  147.92  4968.7  144.01 4974.89  143.71
  4999.6  137.76    5009  140.13  5056.6  143.72    5134  146.38    5174  145.87
    5254  146.95    5294   145.8    5334  146.59    5374  146.06    5415  146.76
    5485   146.1    5675  147.31    5835  148.54    5935  150.65  6128.6  151.93
#Mann= 6 ,-1 , 0
  4045.6     .12       0  4968.7     .06       0  5056.6     .12       0
    5485     .08       0    5675     .12       0  6128.6      .2       0
#XS Ineff= 2 , 0
         4878.66  147.92 5134.35          146.84
Permanent Ineff=
       F       F
Bank Sta=4974.89,5056.6
Exp/Cntr=0.5,0.3

Type RM Length L Ch R = 1 ,3023.0  ,301.83,151.4,125.5
BEGIN DESCRIPTION:
Cross Section xs4.25
END DESCRIPTION:
XS GIS Cut Line= 4
      3051477.35      13957936.6      3051419.54      13956933.2
      3051014.87      13956553.3    3050800.7486   13956022.4754
#Sta/Elev= 30
    4033   152.1    4103   151.5    4133   150.4    4233   148.8    4263   147.5
    4313     147    4493   147.2    4583   145.2    4663   144.5    4723     145
    4783     142    4823   143.3    4873   141.4  4964.1  140.28  4987.6  139.48
  4999.6   136.6  5002.6   136.9    5009  138.97  5056.6  142.56  5198.1   141.8
  5288.1     145  5378.1   146.1  5408.1   147.8  5428.1   148.1  5488.1   146.4
  5623.1   145.9  5763.1   148.8  5973.1   149.7  6033.1   150.7  6165.9   151.3
#Mann= 4 ,-1 , 0
    4033     .12       0  4964.1     .05       0  5056.6     .12       0
  6165.9      .2       0
#XS Ineff= 2 , 0
       0                 5428.05       0  148.09
Permanent Ineff=
       F       F
Bank Sta=4964.1,5056.6
Exp/Cntr=0.5,0.3

Type RM Length L Ch R = 1 ,2871.6  ,126.55,129,119.93
BEGIN DESCRIPTION:
Cross Section 2871.6
Cross Section XS-04-Culvert1-con
END DESCRIPTION:
XS GIS Cut Line= 5
    3052228.1204    13957809.286      3052096.38      13957493.9
      3051438.77      13956823.1      3051092.45       13956492.
      3050883.64      13955952.5
#Sta/Elev= 30
  3889.2   154.1  3929.2     154  3969.2   152.9  4109.2   152.2  4229.8   149.9
  4249.8   148.9  4369.8   148.3  4489.8     146  4689.8   144.7  4815.6   144.9
  4864.4  143.69  4922.5  143.66  4978.3  142.52  4979.5   139.9  4998.3  136.09
  5001.6  136.28  5003.1  137.26  5010.8  137.67  5017.6  140.44  5067.2  145.01
 5081.52  148.27  5101.9  148.91  5289.1   143.9  5323.1  144.35  5439.1   146.4
  5754.5  147.45  5798.3   148.5  6028.3     150  6118.3   151.4  6226.7   151.5
#Mann= 6 ,-1 , 0
  3889.2     .12       0  4922.5     .05       0  5067.2     .12       0
  5323.1     .15       0  5754.5     .12       0  6226.7      .2       0
Bank Sta=4922.5,5067.2
Exp/Cntr=0.5,0.3

Type RM Length L Ch R = 1 ,2742.6  ,50,50,50
BEGIN DESCRIPTION:
Upstream Section of Walden Way Culvert
END DESCRIPTION:
XS GIS Cut Line= 4
      3052366.49      13957760.3      3052271.32      13957474.8
      3051220.78      13956443.3      3051020.67      13955886.4
#Sta/Elev= 30
    3779  150.53  3799.5  151.33  3919.5  151.53  4063.5  149.91  4109.3  148.76
    4117  148.53  4370.4  147.03  4400.4  145.83  4600.4  143.63  4800.4  144.63
  4864.4  143.25  4922.5  143.22  4978.3  142.08  4979.5  139.46  4998.3  135.65
  5001.6  135.84  5003.1  136.82  5010.8  137.23  5017.6     140  5058.2  140.58
  5109.4  143.49  5240.4  146.53  5280.4  146.73  5370.4  145.33  5460.4  145.43
  5572.8  146.13  5788.2  149.29  5892.8  150.63  6105.4  151.45  6164.5  151.83
#Mann= 8 ,-1 , 0
    3779     .12       0  4063.5     .15       0  4109.3     .12       0
    4117     .15       0  4922.5     .07       0  5109.4     .15       0
  5788.2     .12       0  6105.4      .2       0
#XS Ineff= 2 , 0
       0 4987.13  144.14 5012.77       0   144.2
Permanent Ineff=
       F       F
Bank Sta=4922.5,5109.4
Exp/Cntr=0.5,0.3