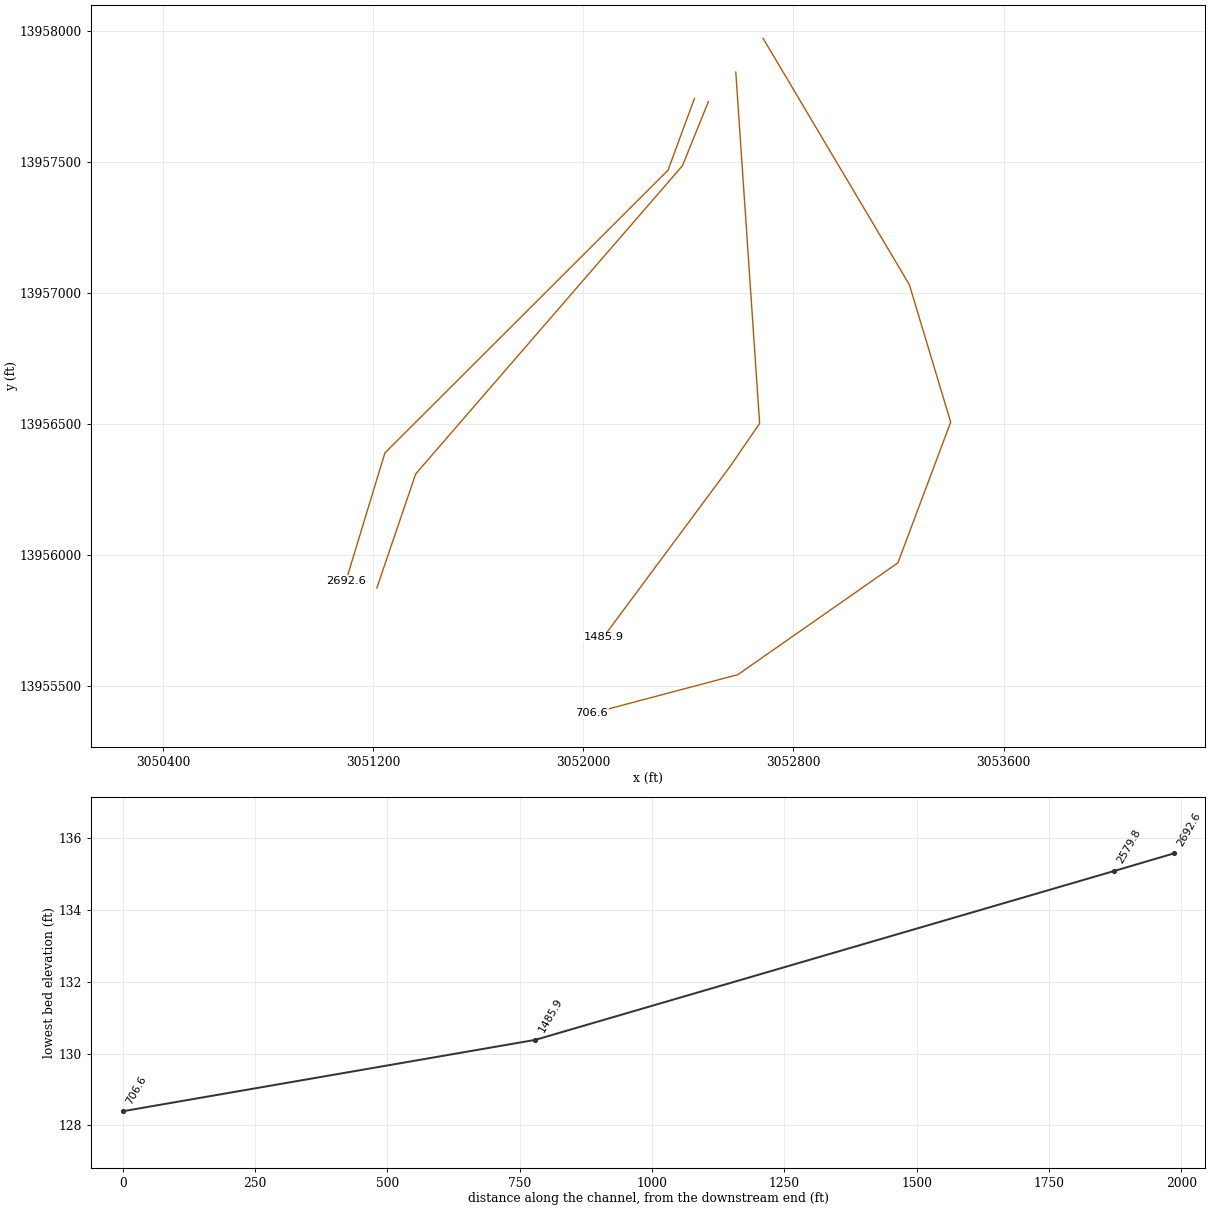
HEC-RAS study M116-00-00.PRJ: M116-00-00

--- M116-00-00.g01 (geometry) --- (continued)

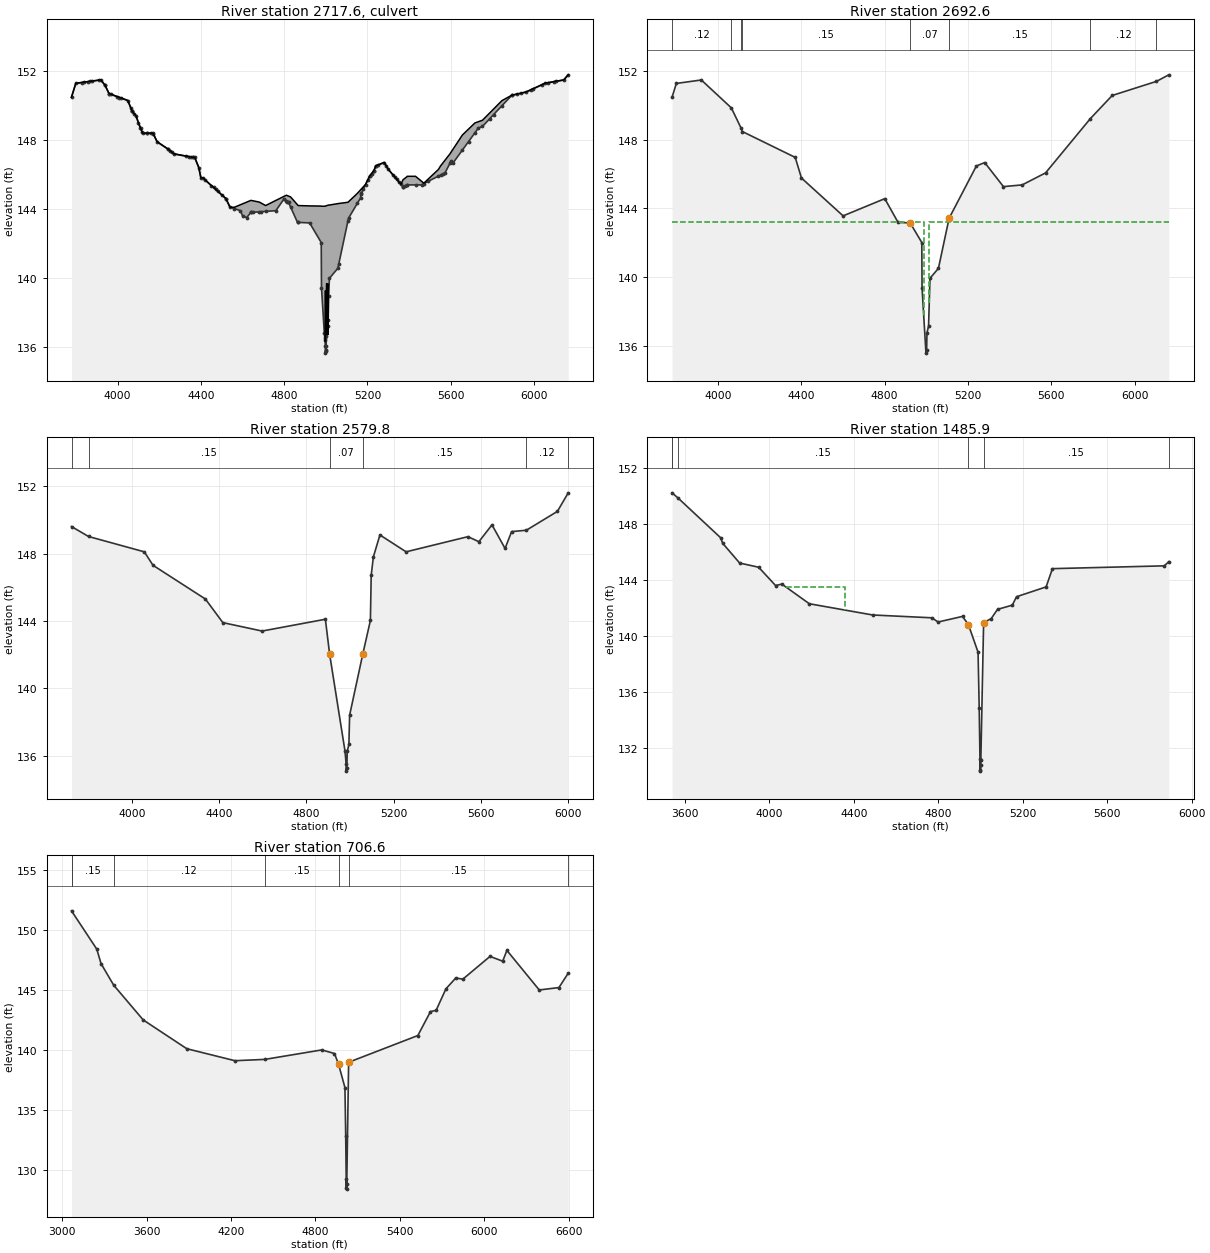
Type RM Length L Ch R = 2 ,2717.6  ,,,
BEGIN DESCRIPTION:
WALDEN WAY
Cross Section 2717.6
Structure ID: M116-00-00-01
END DESCRIPTION:
Bridge Culvert--1,0,-1,-1, 0
Deck Dist Width WeirC Skew NumUp NumDn MinLoCord MaxHiCord MaxSubmerge Is_Ogee
10,30,3,0, 145, 145, , , 0.95, 0, 1,1,,
    3779  3799.5    3829    3839    3859    3869    3879    3909  3919.5    3939
  3939.5    3959  3959.5    3969    3999    4009    4019  4049.5  4063.5    4069
  4069.5  4071.2  4081.2  4089.5  4100.4  4109.3  4111.2    4117  4120.4  4140.4
  4141.2  4161.2  4170.4  4171.2  4190.4  4240.4  4241.2  4250.4  4261.2  4270.4
  4331.2  4341.2  4351.2  4360.4  4361.2  4370.4  4390.4  4400.4  4410.4  4421.2
  4451.2  4461.2  4471.2  4481.2  4501.2  4520.4  4521.2  4540.4  4561.2  4590.4
  4600.4  4620.4  4640.4  4641.2  4681.2  4711.2  4760.4  4800.4  4811.2  4831.2
  4864.4  4867.5  4922.5  4978.3  4979.5  4993.1  4995.4  4996.4  4998.1  4998.3
  4999.4  5001.6  5001.8  5002.8  5003.1  5010.8  5011.5  5014.2  5017.6  5058.2
  5062.7  5106.6  5109.4  5151.2  5181.2  5191.2  5201.2  5210.4  5211.2  5221.2
  5230.4  5231.2  5240.4  5241.2  5251.2  5280.4  5291.2  5300.4  5321.2  5331.2
  5341.2  5351.2  5361.2  5370.4  5371.2  5390.4  5391.2  5431.2  5460.4  5471.2
  5490.4  5541.2  5551.2  5596.2  5602.8  5612.8  5656.2  5716.2  5732.8  5752.8
  5846.2  5892.8  5896.2  5916.2  5936.2  5962.8  5986.2  5996.2  6036.2  6052.8
  6066.2  6096.2  6105.4  6142.8  6164.5
   150.5  151.31  151.36  151.38  151.41  151.43  151.44  151.49  151.51  151.22
  151.21  150.72  150.71  150.67  150.53  150.49  150.45  150.31  149.89  149.73
  149.71  149.68  149.53  149.41  149.01  148.74  148.69  148.51  148.41  148.41
  148.41  148.41  148.41  148.39  147.91   147.5   147.5  147.41   147.3  147.21
  147.07  147.05  147.03  147.01  147.01  147.01  146.41  145.81  145.81  145.69
  145.36  145.26  145.15  145.04  144.82  144.61  144.59   144.1   144.1  144.25
   144.3   144.4   144.5   144.5   144.4   144.2   144.5  144.74   144.8   144.7
  144.24   144.2  144.18  144.17  144.16  144.16  144.16  144.16  144.17  144.17
  144.18  144.19  144.19  144.19  144.19  144.22  144.22  144.23  144.23  144.31
  144.32  144.39  144.42   144.9   145.3  145.43  145.68  145.91  145.92  146.07
  146.21  146.23  146.51  146.51  146.56  146.71  146.49  146.31  146.01  145.87
  145.73  145.58  145.44  145.68   145.7  145.88   145.9   145.9  145.61   145.5
  145.72   146.3   146.5   147.2  147.32   147.5   148.3     149  149.07  149.16
   150.3  150.61  150.62  150.68  150.73  150.81  150.94     151  151.22  151.31
  151.34  151.41  151.43   151.5   151.8
                                                                                
                                                                                
                                                                                
                                                                                
                                                                                
                                                                                
                                                                                
                                                   136.5  136.37  136.04  135.62
  135.74  135.81  136.02  136.61  136.79   137.2  137.56
                                                                                
                                                                                
                                                                                
                                                                                
                                                                                
                                        
    3779  3799.5    3829    3839    3859    3869    3879    3909  3919.5    3939
  3939.5    3959  3959.5    3969    3999    4009    4019  4049.5  4063.5    4069
  4069.5  4071.2  4081.2  4089.5  4100.4  4109.3  4111.2    4117  4120.4  4140.4
  4141.2  4161.2  4170.4  4171.2  4190.4  4240.4  4241.2  4250.4  4261.2  4270.4
  4331.2  4341.2  4351.2  4360.4  4361.2  4370.4  4390.4  4400.4  4410.4  4421.2
  4451.2  4461.2  4471.2  4481.2  4501.2  4520.4  4521.2  4540.4  4561.2  4590.4
  4600.4  4620.4  4640.4  4641.2  4681.2  4711.2  4760.4  4800.4  4811.2  4831.2
  4864.4  4867.5  4922.5  4978.3  4979.5  4993.1  4995.4  4996.4  4998.1  4998.3
  4999.4  5001.6  5001.8  5002.8  5003.1  5010.8  5011.5  5014.2  5017.6  5058.2
  5062.7  5106.6  5109.4  5151.2  5181.2  5191.2  5201.2  5210.4  5211.2  5221.2
  5230.4  5231.2  5240.4  5241.2  5251.2  5280.4  5291.2  5300.4  5321.2  5331.2
  5341.2  5351.2  5361.2  5370.4  5371.2  5390.4  5391.2  5431.2  5460.4  5471.2
  5490.4  5541.2  5551.2  5596.2  5602.8  5612.8  5656.2  5716.2  5732.8  5752.8
  5846.2  5892.8  5896.2  5916.2  5936.2  5962.8  5986.2  5996.2  6036.2  6052.8
  6066.2  6096.2  6105.4  6142.8  6164.5
   150.5  151.31  151.36  151.38  151.41  151.43  151.44  151.49  151.51  151.22
  151.21  150.72  150.71  150.67  150.53  150.49  150.45  150.31  149.89  149.73
  149.71  149.68  149.53  149.41  149.01  148.74  148.69  148.51  148.41  148.41
  148.41  148.41  148.41  148.39  147.91   147.5   147.5  147.41   147.3  147.21
  147.07  147.05  147.03  147.01  147.01  147.01  146.41  145.81  145.81  145.69
  145.36  145.26  145.15  145.04  144.82  144.61  144.59   144.1   144.1  144.25
   144.3   144.4   144.5   144.5   144.4   144.2   144.5  144.74   144.8   144.7
  144.24   144.2  144.18  144.17  144.16  144.16  144.16  144.16  144.17  144.17
  144.18  144.19  144.19  144.19  144.19  144.22  144.22  144.23  144.23  144.31
  144.32  144.39  144.42   144.9   145.3  145.43  145.68  145.91  145.92  146.07
  146.21  146.23  146.51  146.51  146.56  146.71  146.49  146.31  146.01  145.87
  145.73  145.58  145.44  145.68   145.7  145.88   145.9   145.9  145.61   145.5
  145.72   146.3   146.5   147.2  147.32   147.5   148.3     149  149.07  149.16
   150.3  150.61  150.62  150.68  150.73  150.81  150.94     151  151.22  151.31
  151.34  151.41  151.43   151.5   151.8
                                                                                
                                                                                
                                                                                
                                                                                
                                                                                
                                                                                
                                                                                
                                                   136.5  136.37  136.04  135.62
  135.74  135.81  136.02  136.61  136.79   137.2  137.56
                                                                                
                                                                                
                                                                                
                                                                                
                                                                                
                                        
BR Coef= 1 , 0 , 0 ,1.25, 0 ,,,0.8,-1,2,1,
WSPro=,,,, 1 ,,,, 0 ,,,, 0 ,,,,-1 ,-1 ,-1 , 0 , 0 , 0 , 0 , 0
Culvert=1,3,,30,0.015,0.4,1,1,3,136.26,4998.3,135.97,4998.3,Culvert #1  , 0 ,10
Culvert Bottom n=0.015
Culvert=1,3,,30,0.015,0.4,1,1,3,136.68,5004.1,136.08,5004.1,Culvert #2  , 0 ,10
Culvert Bottom n=0.015
Culvert=1,3,,30,0.015,0.4,1,1,3,136.67,5010,136.26,5010,Culvert #3  , 0 ,10
Culvert Bottom n=0.015
BR U #Sta/Elev= 159
    3779   150.5  3799.5   151.3    3829  151.35    3839  151.37    3859   151.4
    3869  151.42    3879  151.43    3909  151.48  3919.5   151.5    3939  151.21
  3939.5   151.2    3959  150.71  3959.5   150.7    3969  150.66    3999  150.52
    4009  150.48    4019  150.44  4049.5   150.3  4063.5  149.88    4069  149.72
  4069.5   149.7  4071.2  149.67  4081.2  149.52  4089.5   149.4  4100.4     149
  4109.3  148.73  4111.2  148.68    4117   148.5  4120.4   148.4  4140.4   148.4
  4141.2   148.4  4161.2   148.4  4170.4   148.4  4171.2  148.38  4190.4   147.9
  4240.4   147.5  4241.2  147.49  4250.4   147.4  4261.2  147.29  4270.4   147.2
  4331.2  147.06  4341.2  147.04  4351.2  147.02  4360.4     147  4361.2     147
  4370.4     147  4390.4   146.4  4400.4   145.8  4410.4   145.8  4421.2  145.68
  4451.2  145.35  4461.2  145.25  4471.2  145.14  4481.2  145.03  4501.2  144.81
  4520.4   144.6  4521.2  144.58  4540.4   144.1  4561.2  144.02  4590.4   143.9
  4600.4   143.6  4620.4   143.5  4640.4   143.8  4641.2   143.8  4651.2  143.81
  4681.2  143.83  4691.2  143.84  4711.2  143.86  4760.4   143.9  4800.4   144.6
  4811.2  144.48  4815.6  144.43  4821.1  144.38  4821.2  144.38  4831.2  144.11
  4864.4  143.22  4867.5  143.22  4922.5  143.19  4978.3  142.05  4979.5  139.43
  4993.1   136.8  4995.4   136.5  4996.4  136.37  4998.1  136.04  4998.3  135.62
  4999.4  135.74  5001.6  135.81  5001.8  136.02  5002.8  136.61  5003.1  136.79
  5010.8   137.2  5011.5  137.56  5014.2  138.94  5017.6  139.97  5058.2  140.55
  5062.7  140.81  5106.6   143.3  5109.4  143.46  5151.2  144.32  5167.5  144.65
  5169.3  144.87  5171.2  144.92  5181.2  145.17  5191.2  145.42  5201.2  145.67
  5210.4   145.9  5211.2  145.91  5221.2  146.06  5230.4   146.2  5231.2  146.22
  5240.4   146.5  5241.2   146.5  5251.2  146.55  5280.4   146.7  5291.2  146.48
  5300.4   146.3  5321.2     146  5331.2  145.86  5341.2  145.72  5351.2  145.57
  5361.2  145.43  5370.4   145.3  5371.2   145.3  5381.2  145.35  5390.4   145.4
  5391.2   145.4  5431.2   145.4  5460.4   145.4  5471.2  145.47  5490.4   145.6
  5541.2  145.91  5551.2  145.97  5561.2  146.03  5572.8   146.1  5596.2  146.65
  5602.8   146.8  5612.8   146.7  5656.2  147.42  5686.2  147.92  5716.2  148.42
  5732.8   148.7  5752.8   148.8  5788.2  149.26  5806.2  149.49  5846.2     150
  5892.8   150.6  5896.2  150.61  5916.2  150.67  5936.2  150.72  5962.8   150.8
  5986.2  150.93  5996.2  150.99  6036.2  151.21  6052.8   151.3  6066.2  151.33
  6096.2   151.4  6105.4  151.42  6142.8   151.5  6164.5   151.8
BR U #Mann= 9
    3779      .2    3779     .12  4063.5     .15  4109.3     .12    4117     .15
  4922.5     .07  5109.4     .15  5788.2     .12  6105.4      .2
BR U Banks=4922.5,5109.4
BR D #Sta/Elev= 159
    3779   150.5  3799.5   151.3    3829  151.35    3839  151.37    3859   151.4
    3869  151.42    3879  151.43    3909  151.48  3919.5   151.5    3939  151.21
  3939.5   151.2    3959  150.71  3959.5   150.7    3969  150.66    3999  150.52
    4009  150.48    4019  150.44  4049.5   150.3  4063.5  149.88    4069  149.72
  4069.5   149.7  4071.2  149.67  4081.2  149.52  4089.5   149.4  4100.4     149
  4109.3  148.73  4111.2  148.68    4117   148.5  4120.4   148.4  4140.4   148.4
  4141.2   148.4  4161.2   148.4  4170.4   148.4  4171.2  148.38  4190.4   147.9
  4240.4   147.5  4241.2  147.49  4250.4   147.4  4261.2  147.29  4270.4   147.2
  4331.2  147.06  4341.2  147.04  4351.2  147.02  4360.4     147  4361.2     147
  4370.4     147  4390.4   146.4  4400.4   145.8  4410.4   145.8  4421.2  145.68
  4451.2  145.35  4461.2  145.25  4471.2  145.14  4481.2  145.03  4501.2  144.81
  4520.4   144.6  4521.2  144.58  4540.4   144.1  4561.2  144.02  4590.4   143.9
  4600.4   143.6  4620.4   143.5  4640.4   143.8  4641.2   143.8  4651.2  143.81
  4681.2  143.83  4691.2  143.84  4711.2  143.86  4760.4   143.9  4800.4   144.6
  4811.2  144.48  4815.6  144.43  4821.1  144.38  4821.2  144.38  4831.2  144.11
  4864.4  143.22  4867.5  143.22  4922.5  143.19  4978.3  142.05  4979.5  139.43
  4993.1   136.8  4995.4   136.5  4996.4  136.37  4998.1  136.04  4998.3  135.62
  4999.4  135.74  5001.6  135.81  5001.8  136.02  5002.8  136.61  5003.1  136.79
  5010.8   137.2  5011.5  137.56  5014.2  138.94  5017.6  139.97  5058.2  140.55
  5062.7  140.81  5106.6   143.3  5109.4  143.46  5151.2  144.32  5167.5  144.65
  5169.3  144.87  5171.2  144.92  5181.2  145.17  5191.2  145.42  5201.2  145.67
  5210.4   145.9  5211.2  145.91  5221.2  146.06  5230.4   146.2  5231.2  146.22
  5240.4   146.5  5241.2   146.5  5251.2  146.55  5280.4   146.7  5291.2  146.48
  5300.4   146.3  5321.2     146  5331.2  145.86  5341.2  145.72  5351.2  145.57
  5361.2  145.43  5370.4   145.3  5371.2   145.3  5381.2  145.35  5390.4   145.4
  5391.2   145.4  5431.2   145.4  5460.4   145.4  5471.2  145.47  5490.4   145.6
  5541.2  145.91  5551.2  145.97  5561.2  146.03  5572.8   146.1  5596.2  146.65
  5602.8   146.8  5612.8   146.7  5656.2  147.42  5686.2  147.92  5716.2  148.42
  5732.8   148.7  5752.8   148.8  5788.2  149.26  5806.2  149.49  5846.2     150
  5892.8   150.6  5896.2  150.61  5916.2  150.67  5936.2  150.72  5962.8   150.8
  5986.2  150.93  5996.2  150.99  6036.2  151.21  6052.8   151.3  6066.2  151.33
  6096.2   151.4  6105.4  151.42  6142.8   151.5  6164.5   151.8
BR D #Mann= 9
    3779      .2    3779     .12  4063.5     .15  4109.3     .12    4117     .15
  4922.5     .07  5109.4     .15  5788.2     .12  6105.4      .2
BR D Banks=4922.5,5109.4
BC Design=,, 0 ,, 0 ,,,,,,
BC HTab HWMax=151.83

Type RM Length L Ch R = 1 ,2692.6  ,112.8,112.8,112.8
BEGIN DESCRIPTION:
Downstream Section of Walden Way Culvert
END DESCRIPTION:
XS GIS Cut Line= 4
       3052423.5      13957742.1      3052322.74      13957467.8
      3051244.81       13956389.      3051096.91      13955901.8
#Sta/Elev= 30
    3779  150.46  3799.5  151.26  3919.5  151.46  4063.5  149.84  4109.3  148.69
    4117  148.46  4370.4  146.96  4400.4  145.76  4600.4  143.56  4800.4  144.56
  4864.4  143.18  4922.5  143.15  4978.3  142.01  4979.5  139.39  4998.3  135.58
  5001.6  135.77  5003.1  136.75  5010.8  137.16  5017.6  139.93  5058.2  140.51
  5109.4  143.42  5240.4  146.46  5280.4  146.66  5370.4  145.26  5460.4  145.36
  5572.8  146.06  5788.2  149.22  5892.8  150.56  6105.4  151.38  6164.5  151.76
#Mann= 8 ,-1 , 0
    3779     .12       0  4063.5     .15       0  4109.3     .12       0
    4117     .15       0  4922.5     .07       0  5109.4     .15       0
  5788.2     .12       0  6105.4      .2       0
#XS Ineff= 2 , 0
       0 4987.99  143.19 5014.07       0   143.2
Permanent Ineff=
       F       F
Bank Sta=4922.5,5109.4
Exp/Cntr=0.5,0.3

Type RM Length L Ch R = 1 ,2579.8  ,815.35,1093.9,976.25
BEGIN DESCRIPTION:
Cross Section 2579.8
Cross Section XS-03-Culvert1-exp
END DESCRIPTION:
XS GIS Cut Line= 4
      3052476.47      13957729.5      3052377.69       13957485.
      3051362.16      13956309.3      3051214.25      13955874.2
#Sta/Elev= 30
  3723.4   149.6  3801.4  149.01  4057.1   148.1  4097.1   147.3  4337.1   145.3
  4417.1   143.9  4597.1   143.4  4887.1   144.1 4906.55  142.03 4977.15  136.27
 4982.15  135.51 4982.35  135.09 4985.65  135.28 4987.15  136.26 4994.85  136.67
 4998.25  138.41 5058.17  142.01 5093.45  144.03  5097.1   146.7  5107.1   147.8
  5137.1   149.1  5257.1   148.1  5540.7     149  5590.7   148.7  5650.7   149.7
  5710.7   148.3  5740.7   149.3  5808.2  149.38  5950.7   150.5  6000.2   151.6
#Mann= 6 ,-1 , 0
  3723.4     .12       0  3801.4     .15       0 4906.55     .07       0
 5058.17     .15       0  5808.2     .12       0  6000.2      .2       0
Bank Sta=4906.55,5058.17
Exp/Cntr=0.3,0.1

Type RM Length L Ch R = 1 ,1485.9  ,724.34,779.3,727.72
BEGIN DESCRIPTION:
Cross Section 1485.9
Cross Section XS-02
END DESCRIPTION:
XS GIS Cut Line= 4
      3052580.78       13957842.       3052671.5       13956502.
      3052559.71      13956338.4      3052076.95      13955686.7
#Sta/Elev= 30
  3539.5   150.2  3567.8  149.83  3769.5     147  3779.5   146.6  3859.5   145.2
  3949.5   144.9  4029.5   143.6  4059.5   143.7  4189.5   142.3  4489.5   141.5
  4769.5   141.3  4799.5     141  4914.9   141.4  4942.8  140.81  4988.5  138.85
  4993.9  134.85  4998.3  130.47  4998.4  131.25  4999.7  130.38  5001.5  130.84
  5001.6  131.15  5014.8  140.96  5050.5  141.24  5080.7   141.9  5150.7   142.2
  5170.7   142.8  5310.7   143.5  5340.7   144.8  5870.7     145  5891.7   145.3
#Mann= 6 , 1 , 0
  3539.5      .2       0  3539.5     .12       0  3567.8     .15       0
  4942.8     .07       0  5014.8     .15       0  5891.7      .2       0
#XS Ineff= 1 ,-1
 4083.11 4357.91   143.5
Permanent Ineff=
       F
Bank Sta=4942.8,5014.8
Exp/Cntr=0.3,0.1

Type RM Length L Ch R = 1 ,706.6   ,0,0,0
BEGIN DESCRIPTION:
Cross Section 706.6
Cross Section XS-01
END DESCRIPTION:
XS GIS Cut Line= 6
      3052684.62       13957971.      3053241.45      13957031.4
      3053398.87      13956506.7      3053197.95       13955970.
      3052588.92      13955543.6      3052032.09      13955395.7
#Sta/Elev= 30
    3065   151.6    3245   148.4    3275   147.2    3365   145.4    3575   142.5
    3885   140.1  4227.2   139.1    4440  139.21  4845.1     140  4935.1   139.7
    4964  138.82  5009.7  136.86  5015.1  132.86  5019.5  128.48  5019.6  129.26
  5020.9  128.39  5022.7  128.85    5036  138.97  5528.2   141.2  5618.2   143.2
  5658.2   143.3  5728.2   145.1  5798.2     146  5848.2   145.9  6041.6   147.8
  6131.6   147.4  6161.6   148.3  6391.6     145  6531.6   145.2  6597.7   146.4
#Mann= 7 , 1 , 0
    3065      .2       0    3065     .15       0    3365     .12       0
    4440     .15       0    4964     .07       0    5036     .15       0
  6597.7      .2       0
Bank Sta=4964,5036
Exp/Cntr=0.3,0.1

Chan Stop Cuts=-1
Use User Specified Reach Order=0
User Specified Reach Order=M116-00-00      ,Reach - 1